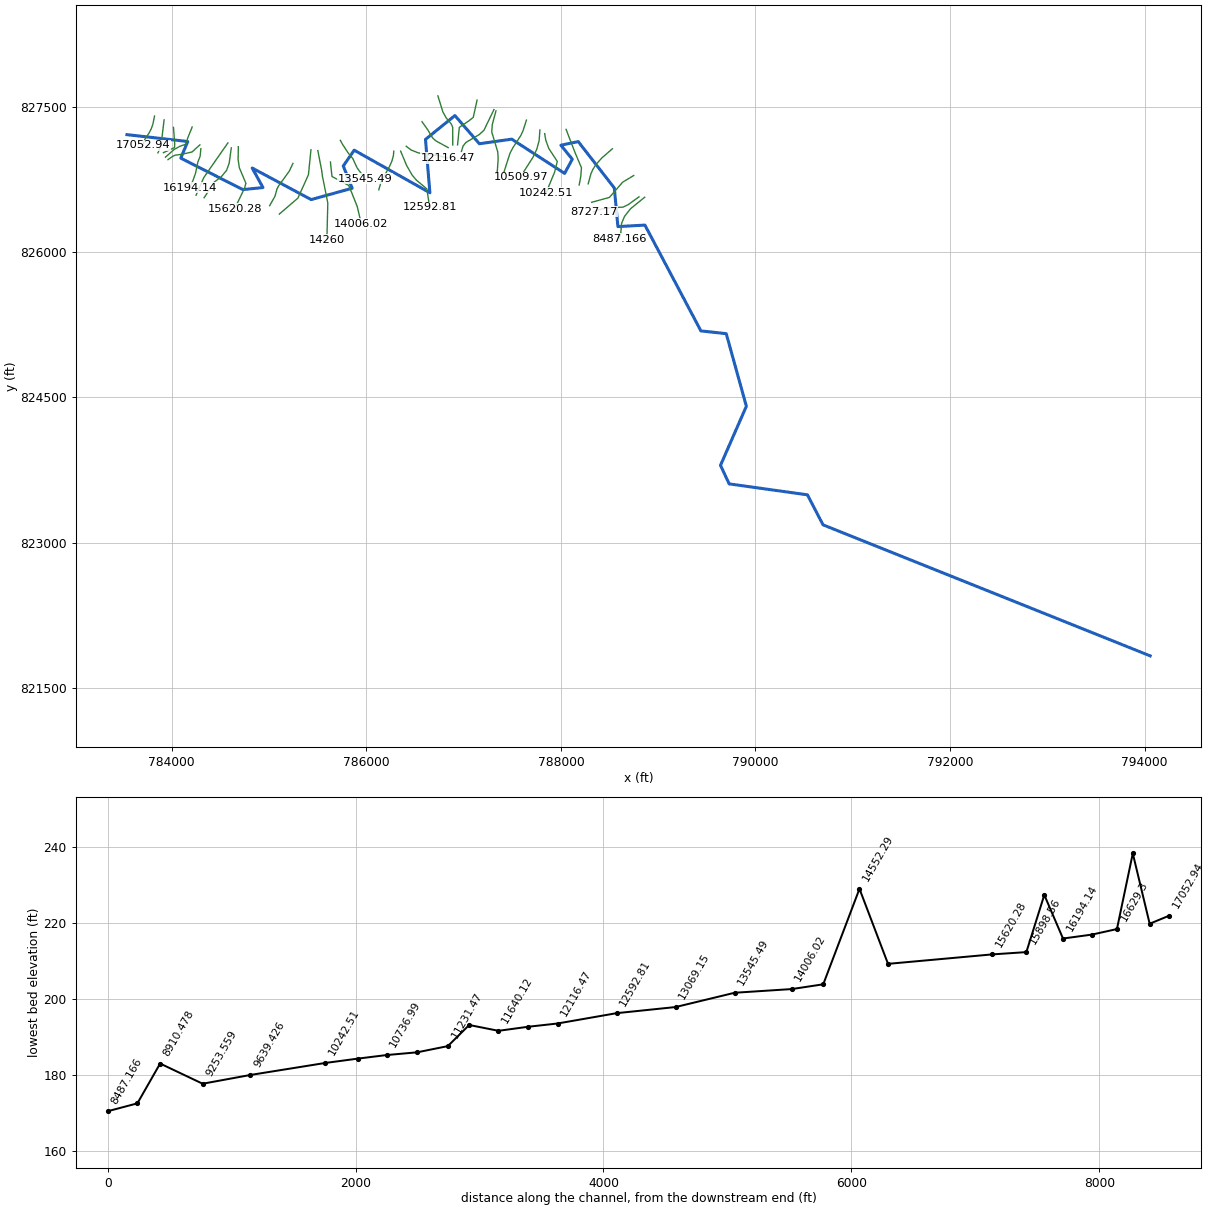
--- 18178_ras.prj (project) ---

Proj Title=18178
Current Plan=p01
Default Exp/Contr=0.3,0.1
English Units
Geom File=g01
Flow File=f01
Plan File=p01
Y Axis Title=Elevation
X Axis Title(PF)=Main Channel Distance
X Axis Title(XS)=Station
BEGIN DESCRIPTION:
RFD model 18178 exported to HEC-RAS
END DESCRIPTION:

--- 18178_ras.p01 (plan) ---

Plan Title=Plan 01
Program Version=4.10
Short Identifier=Plan 01
Geom File=g01
Flow File=f01
Subcritical Flow
Calc Critical at every XS
Secant Critical Depth

--- 18178_ras.f01 (steady flow) ---

Flow Title=Flow 01
Program Version=5.01
Number of Profiles= 6
Profile Names=10yr,25yr,50yr,100yr,100plus,500yr
River Rch & RM=18178,49,17052.94
 1493.68 2494.98 3470.75 4397.41 6420.22 8519.33
River Rch & RM=18178,49, 16893.3
 1511.34 2524.84 3512.66 4450.86 6498.25 8609.56
River Rch & RM=18178,49,16757.14
 1512.36 2526.59 3515.13 4454.03 6502.89 8614.99
River Rch & RM=18178,49, 16629.3
 1512.98 2527.65 3516.62 4455.93 6505.66 8618.24
River Rch & RM=18178,49,16194.14
 1519.15 2538.17 3531.47 4474.97 6533.46 8650.75
River Rch & RM=18178,49,16043.27
 1524.38 2547.05 3543.97 4490.94 6556.78 8677.81
River Rch & RM=18178,49,15898.56
 1690.61 2829.58 3941.78 4999.72 7299.59 9534.31
River Rch & RM=18178,49,15620.28
 1693.02 2833.69 3947.59 5007.16 7310.45 9546.82
River Rch & RM=18178,49,14782.52
 1808.53 3027.43  4218.1 5350.44 7811.6510106.12
River Rch & RM=18178,49,14552.29
 1825.33  3056.3 4259.05 5403.13 7888.5710194.59
River Rch & RM=18178,49,   14260
 1828.42 3061.61 4266.57 5412.82 7902.7110210.83
River Rch & RM=18178,49,14006.02
 1832.67 3068.91 4276.92 5426.12 7922.1410233.14
River Rch & RM=18178,49,13545.49
 1864.83  3123.6 4353.98 5524.71 8066.0810395.85
River Rch & RM=18178,49,13069.15
 1868.48 3129.88 4362.88 5536.16 8082.7910414.98
River Rch & RM=18178,49,12592.81
 1874.65 3140.47 4377.87 5555.45 8110.9610447.18
River Rch & RM=18178,49,12116.47
 1878.31 3146.75 4386.77  5566.9 8127.6710466.28
River Rch & RM=18178,49,11878.29
    1882 3153.07 4395.72 5578.39 8144.4410485.36
River Rch & RM=18178,49,11640.12
  1893.9 3173.23 4424.06 5614.55 8197.2510544.53
River Rch & RM=18178,49,11403.89
 1896.73 3178.02 4430.78 5623.14 8209.7810558.56
River Rch & RM=18178,49,11231.47
 1923.81 3223.85 4495.15 5705.25 8329.66 10692.4
River Rch & RM=18178,49,10984.23
 1925.15 3226.15 4498.41 5709.44 8335.7810699.37
River Rch & RM=18178,49,10736.99
 1926.69 3228.79 4502.15 5714.25  8342.810707.34
River Rch & RM=18178,49,10509.97
 2082.81 3489.57 4865.33 6173.93 9013.9411436.63
River Rch & RM=18178,49,10242.51
 2086.05 3495.11 4873.18 6184.01 9028.6511453.12
River Rch & RM=18178,49,9639.426
 2099.91 3518.59 4906.17 6226.11 9090.1211520.93
River Rch & RM=18178,49,9253.559
 2102.98 3523.83 4913.58 6235.61 9103.9811536.41
River Rch & RM=18178,49,8910.478
 2252.93 3774.39 5262.62 6677.46 9749.0912229.47
River Rch & RM=18178,49, 8727.17
 2254.25 3776.65 5265.82 6681.55 9755.0712236.09
River Rch & RM=18178,49,8487.166
  2256.9 3781.17 5272.21 6689.75 9767.0312249.32
River Rch & RM=18178,49,  8237.3
 2265.98 3796.68 5294.12 6717.84 9808.0512294.62
River Rch & RM=18178,49,8007.159
 2333.62 3912.93 5459.02 6930.0310117.84 12638.9
River Rch & RM=18178,49,7731.383
 2337.19 3919.02 5467.63 6941.0610133.9512656.62
River Rch & RM=18178,49, 7505.49
 2342.34 3927.87 5480.18 6957.2110157.5212682.72
River Rch & RM=18178,49,7327.675
 2347.29 3936.39 5492.26 6972.7510180.2112707.87
River Rch & RM=18178,49,7047.144
 2350.96 3942.69  5501.2 6984.2610197.0212726.49
River Rch & RM=18178,49, 6807.14
 2398.33  4024.2 5616.92 7133.2710414.5712967.53
River Rch & RM=18178,49,6420.004
 2534.98 4255.88 5942.76 7549.2911021.9613622.45
River Rch & RM=18178,49,6327.132
 2536.24 4258.05 5945.84 7553.2611027.7613628.79
River Rch & RM=18178,49,6214.935
 2537.87 4260.85 5949.81 7558.3611035.2113636.94
River Rch & RM=18178,49,5880.988
 2542.56 4268.91 5961.25 7573.08 11056.713660.48
River Rch & RM=18178,49,5652.418
 2544.33 4271.97 5965.61 7578.7111064.9113669.53
River Rch & RM=18178,49,5423.848
  2552.5 4286.07 5985.67 7604.5811102.6913711.12
River Rch & RM=18178,49, 5226.61
  2557.8 4295.23  5998.7 7621.4111127.2613738.22
River Rch & RM=18178,49, 4904.82
 4500.04 7544.0310529.6113358.5819503.5322158.15
River Rch & RM=18178,49,4671.349
 4503.63 7550.2610538.51 13370.119520.3422175.36
River Rch & RM=18178,49,4437.878
  4505.5 7553.5110543.1613376.1119529.1222184.34
River Rch & RM=18178,49,    4281
 4507.22 7556.4910547.4113381.6119537.1622192.57
Boundary for River Rch & Prof#=18178,49,1
Up Type= 0
Dn Type= 2
Boundary for River Rch & Prof#=18178,49,2
Up Type= 0
Dn Type= 2
Boundary for River Rch & Prof#=18178,49,2
Up Type= 0
Dn Type= 2
Boundary for River Rch & Prof#=18178,49,2
Up Type= 0
Dn Type= 2
Boundary for River Rch & Prof#=18178,49,2
Up Type= 0
Dn Type= 2
Boundary for River Rch & Prof#=18178,49,2
Up Type= 0
Dn Type= 2

--- 18178_ras.g01 (geometry) ---

Geom Title=18178
Program Version=4.10

River Reach=18178,49
Reach XY= 30
783540.361856969827213.555189974784165.066937688827142.842751923
 784093.59397924 826970.78720678784731.472726795826646.344286437
784938.313697516826667.154506054784827.325859577826868.950575066
785433.344679326826542.923801071 785855.22458604826660.217766176
785763.531808588826889.630895754785875.794411719827053.272785327
786653.863372267826613.275216083786608.488548369827164.312322848
786910.870272042827410.646897764787162.165600984827119.639239146
787495.058159501827166.931929542788038.210801335826813.251851623
788117.232396992826960.389418796788000.303289565827104.189201487
788178.172686073827142.061720129788549.202107223826662.740217021
788586.006019503826264.151565125788863.750337752826279.789452773
 789439.04326123825187.202562565789699.439700484825158.728890247
789906.309322211824409.316639905789640.410950333823799.159526748
789729.570969224823607.658484257790533.834384323 823494.80635149
790694.193578808823185.065888858794056.137521683821832.185437506

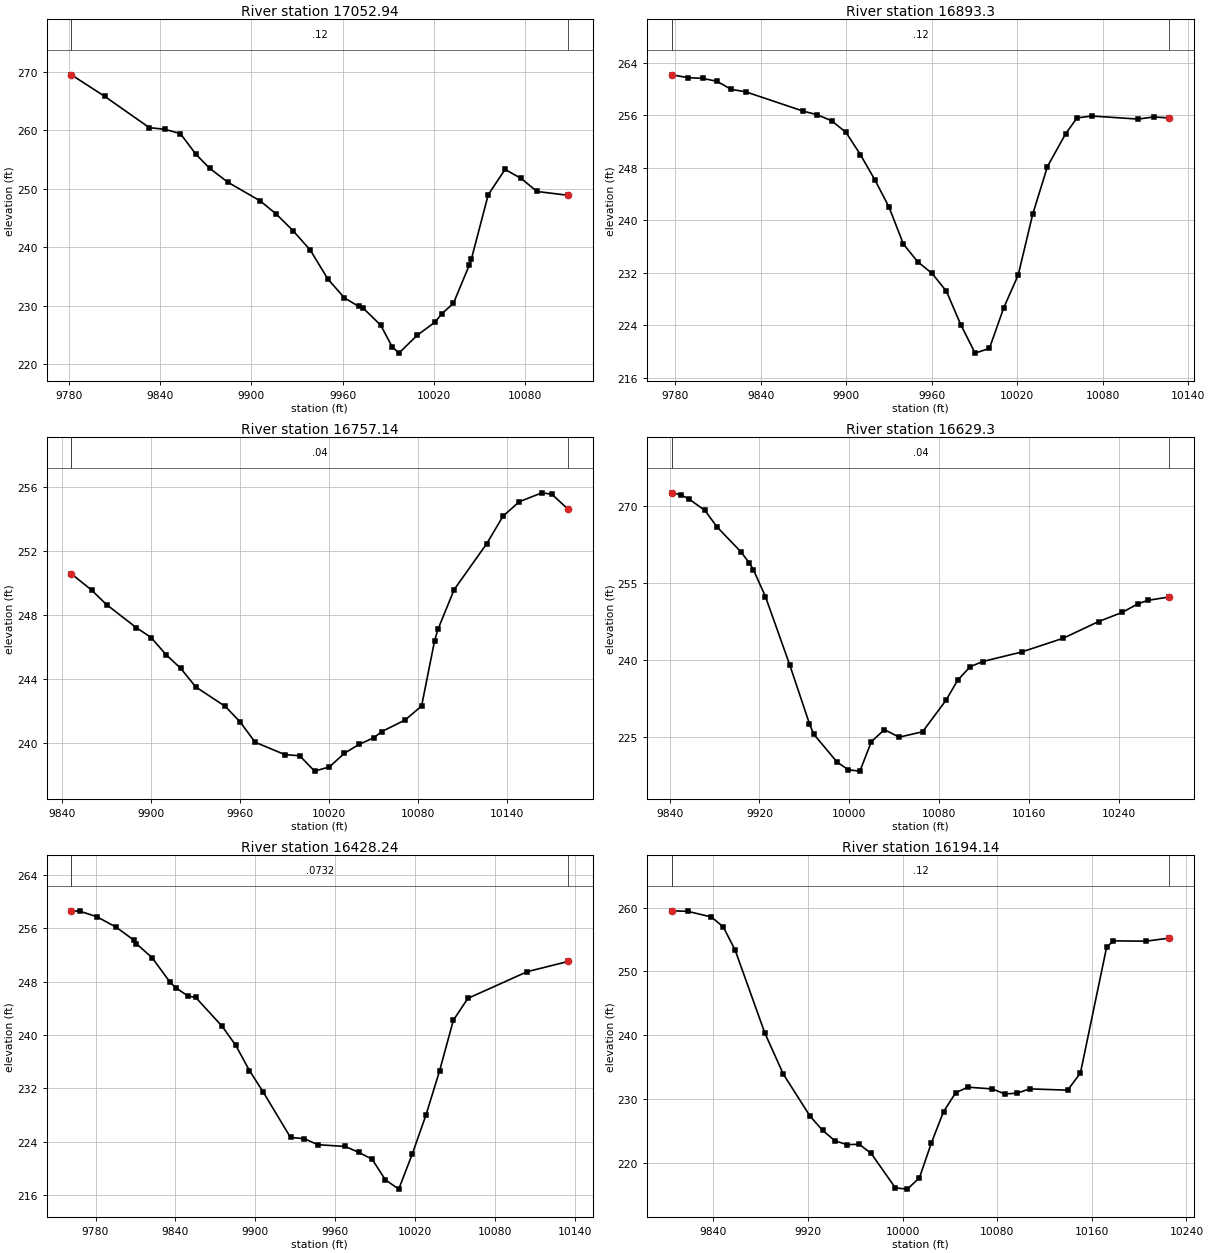
Type RM Length L Ch R = 1 ,17052.94,159.644100,159.644100,159.644100
XS GIS Cut Line= 6
783823.546440868827405.394193491783806.693119813827321.036955052
783789.792778999827273.516975026783769.543578749827234.042272371
783724.935594027827166.070969743783704.779929881827104.721149227
#Sta/Elev= 30
 9781.49269.44479803.368265.7733 9832.78260.42349843.025260.13129853.269259.3899
9863.514255.85439872.627253.44549884.595251.07739905.822247.89049916.436245.6343
9927.582242.76129938.821239.4783 9950.42234.51379961.299231.32149970.654229.8569
9973.192229.67429985.155226.65619992.669222.9657 9997.16221.877710009.11224.9186
10021.06227.200410025.29228.596910033.01230.379310043.56236.982110044.87237.9753
10055.96248.961910067.01253.267810077.53251.756910088.05249.504610108.67248.8512
#Mann= 3 , 0 , 0
 9781.49    0.12       0 9781.49    0.12       010108.67    0.12       0
#XS Ineff= 2 , 0
       0                               0
Bank Sta=9781.49,10108.67
Exp/Cntr=0.3,0.1

Type RM Length L Ch R = 1 , 16893.3,136.153000,136.153000,136.153000
XS GIS Cut Line= 6
783922.023056753827366.281467723783895.076476373827137.830034638
783891.147474874827114.341978078783879.889234827827074.588423668
 783862.93365723827034.190605756783858.169398007827025.482395353
#Sta/Elev= 30
9777.589262.2001 9788.95261.7587 9799.02261.6619 9809.09261.2172 9819.16259.9782
 9829.23 259.6149869.511256.66879879.582256.10529889.652255.18619899.722253.4167
9909.792250.03399919.862246.22339929.933 242.0099940.003236.37719950.073233.6712
9960.143231.89329970.214229.17839980.284224.08129990.354219.727810000.42220.4483
 10010.5226.659210020.63231.651910030.77240.884310041.15248.2007   10054253.2262
10061.94255.623310072.33255.913810104.85255.446910115.69255.7719 10126.5255.6252
#Mann= 3 , 0 , 0
9777.589    0.12       09777.589    0.12       0 10126.5    0.12       0
#XS Ineff= 2 , 0
       0                               0
Bank Sta=9777.589,10126.5
Exp/Cntr=0.3,0.1

Type RM Length L Ch R = 1 ,16757.14,127.847000,127.847000,127.847000
XS GIS Cut Line= 4
784018.717610002827288.623417825784030.813192636827121.195089474
784029.539973438827079.815464601783914.950242966827027.613476276
#Sta/Elev= 30
9846.097250.54279859.756249.52739869.782 248.6239889.834247.1859 9899.86 246.565
9909.886245.49789919.913244.63149929.939243.47939949.991 242.2559960.017241.2753
9970.043 240.0219990.095239.246110000.12239.175210010.15238.214810020.16238.4779
10030.16239.324910040.17239.888110050.17240.304410055.36240.680410071.34241.4175
10082.33242.2884 10091.1246.370110093.32247.068810104.31249.562510126.28252.4337
10137.27254.152810148.26255.054410163.46255.607210170.24255.517110181.28254.5658
#Mann= 3 , 0 , 0
9846.097    0.04       09846.097    0.04       010181.28    0.04       0
#XS Ineff= 2 , 0
       09946.735        10044.59       0
Bank Sta=9846.097,10181.28
Exp/Cntr=0.3,0.1

Type RM Length L Ch R = 1 , 16629.3,201.058500,201.058500,201.058500
XS GIS Cut Line= 6
 784210.68144566 827292.18007027784164.758784398827178.004446027
784146.318324182827115.053099792784085.249276075 827093.73605619
784026.033354022827061.097277709 783936.04994713826981.056224172
#Sta/Elev= 30
9842.111 272.487 9849.85272.10369857.336271.26619871.407269.05159882.186265.8447
9903.743260.93929910.933258.82999914.521257.5514  9925.3252.29569946.857239.0556
9964.529 227.5379968.309225.52699989.103220.09129999.284218.575410009.47218.3311
10019.67224.076610031.32226.409710044.39224.942310065.28225.987210086.16232.1273
10096.62236.051210107.65 238.63410118.68239.647610153.51241.511710190.49244.1824
10222.12247.439110243.35249.243710257.08250.878210265.79251.555810284.79252.2153
#Mann= 3 , 0 , 0
9842.111    0.04       09842.111    0.04       010284.79    0.04       0
#XS Ineff= 2 , 0
       0                               0
Bank Sta=9842.111,10284.79
Exp/Cntr=0.3,0.1

Type RM Length L Ch R = 1 ,16428.24,234.101900,234.101900,234.101900
XS GIS Cut Line= 6
  784289.6871773827107.938239887784209.826066196827035.021573216
784112.786600332827012.149259881784037.527995933 827001.78094143
784011.274585846826990.713965846783962.130723188826955.607132656
#Sta/Elev= 30
9761.878258.61029768.225258.55189781.067257.72159795.308256.17719808.849254.2099
9810.729253.6679 9822.39251.60029835.931247.9099 9840.39247.05399849.473245.8243
9855.221245.61889874.978241.31019885.252238.43959895.526234.6618  9905.8231.4587
9926.348224.62769936.622224.44729946.896223.54299967.445 223.2759977.527222.3922
9987.555221.37989997.583218.268110007.61216.879910017.77222.1578   10028227.9707
10038.23234.609410048.61 242.21210059.46  245.4810104.04249.488710134.87 251.026
#Mann= 3 , 0 , 0
9761.878  0.0732       09761.878  0.0732       010134.87  0.0732       0
#XS Ineff= 2 , 0
       0                               0
Bank Sta=9761.878,10134.87
Exp/Cntr=0.3,0.1

Type RM Length L Ch R = 1 ,16194.14,150.862800,150.862800,150.862800
XS GIS Cut Line= 6
784299.914146543 827068.07051596784292.218809813826989.975120127
784269.623254836826932.815127492 784244.40856722826812.378820524
784217.469127893826736.159453019 784184.89607031826667.281475274
#Sta/Elev= 30
9804.974259.48439818.108259.40889838.205258.52359848.253256.96479858.301253.3361
9883.447240.31829899.112  233.869921.641227.29799932.201225.0711 9942.76223.4138
9953.034222.82249963.227222.8772 9973.42221.43449993.807216.036110003.99215.8442
10014.18217.630210024.37223.136810034.59228.001110044.88230.969410055.16231.8326
10075.87231.555110086.35230.768110096.83230.888810107.35231.563510139.54231.3649
10150.31234.045710172.43253.746910178.19254.774710205.61254.722510225.21255.1984
#Mann= 3 , 0 , 0
9804.974    0.12       09804.974    0.12       010225.21    0.12       0
#XS Ineff= 2 , 0
       0                10068.55       0
Bank Sta=9804.974,10225.21
Exp/Cntr=0.3,0.1

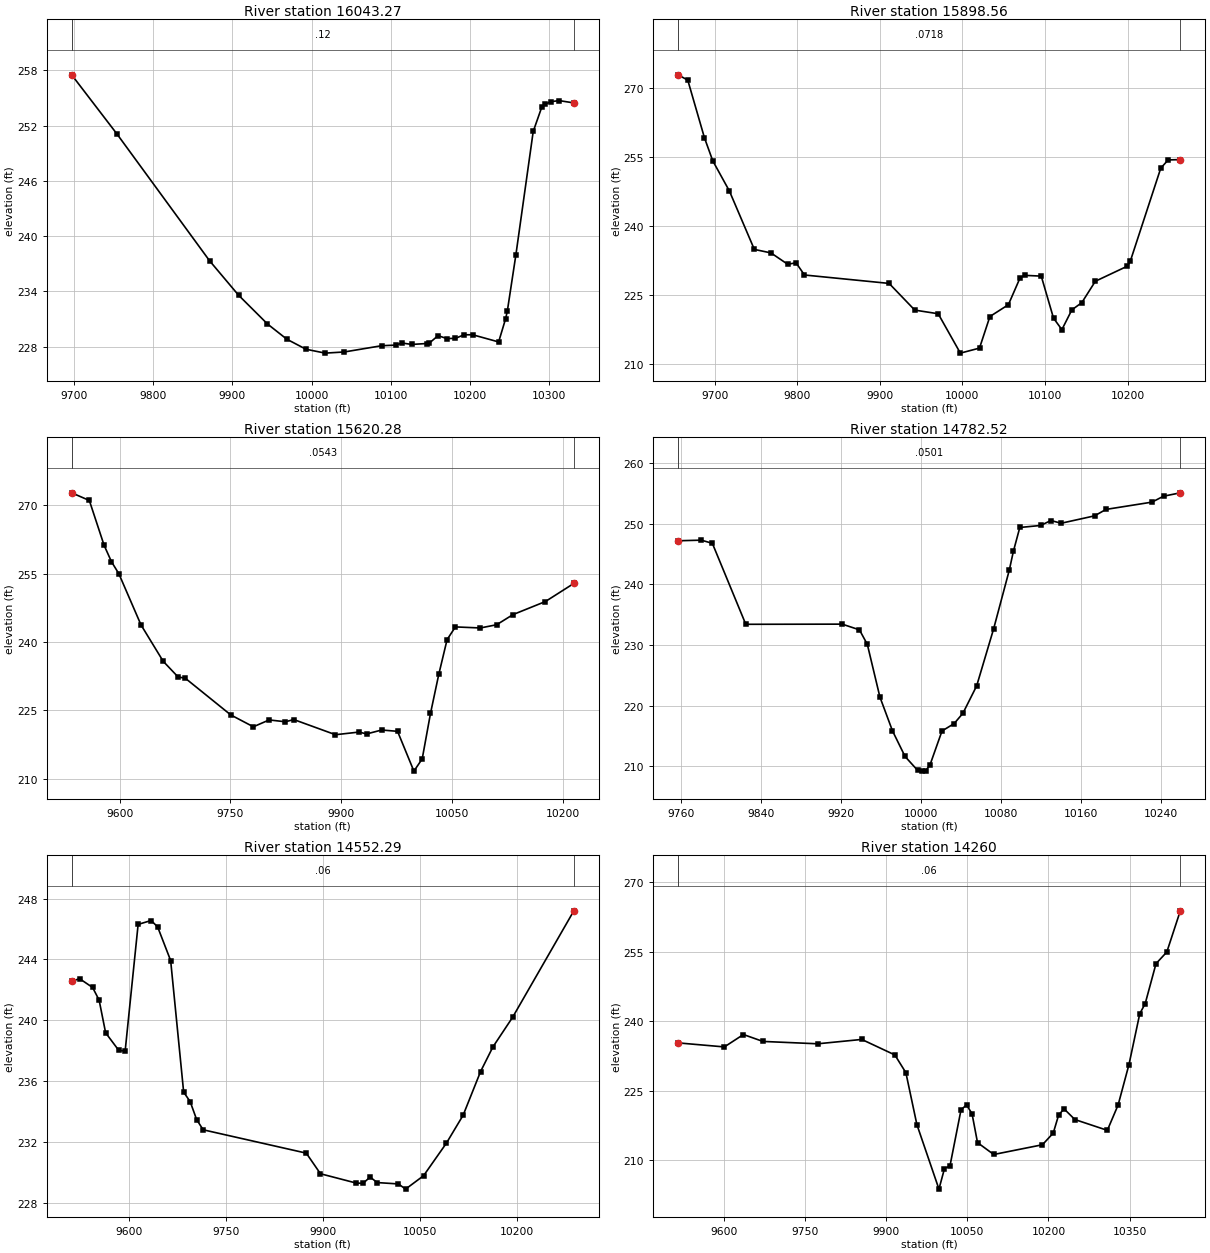
Type RM Length L Ch R = 1 ,16043.27,144.717400,144.717400,144.717400
XS GIS Cut Line= 4
784577.691924304827127.966349289784423.178035408 826905.74412705
784330.296090961826770.327460378784250.434979856826588.035793722
#Sta/Elev= 30
9697.002257.50889754.268251.07969871.131237.3214 9907.67233.5908 9944.21230.4641
9968.565228.81519992.818227.721410017.07227.301110041.32227.4286 10088.2228.1046
10105.88228.170610114.08228.398610126.21228.245210145.07228.342510148.61228.4004
10159.52229.198910170.44228.884710181.36228.902810192.28229.292510203.19229.2946
10235.95228.516110244.75231.027310246.86231.822910257.78237.995710279.62251.3652
10290.53254.031610294.59254.289610301.45 254.59110312.37254.709710330.89254.4613
#Mann= 3 , 0 , 0
9697.002    0.12       09697.002    0.12       010330.89    0.12       0
#XS Ineff= 2 , 0
       0                10136.73       0
Bank Sta=9697.002,10330.89
Exp/Cntr=0.3,0.1

Type RM Length L Ch R = 1 ,15898.56,278.274200,278.274200,278.274200
XS GIS Cut Line= 6
784612.606935002827076.618438515784591.000066268826919.082059696
784563.903278446826844.384876671784509.564375486826778.159900798
784437.806669149826724.281462217784333.577910687826562.098980292
#Sta/Elev= 30
9655.597272.78669667.306271.62849687.462259.1171 9697.54254.09949717.695247.5339
9747.929234.82699768.085234.06219788.308231.59799798.471231.91359808.635229.2629
9911.203227.43229942.287221.62799970.646220.83599997.511212.2734 10020.7213.3659
 10033.3220.232810055.67222.7999 10069.8 228.619 10075.3 229.18410095.51229.0205
10110.37 219.876 10120.5217.384910132.57221.675610144.63223.251410161.05227.9023
10199.77231.180710203.35232.246510240.29252.494610249.24254.280810263.96254.3564
#Mann= 3 , 0 , 0
9655.597  0.0718       09655.597  0.0718       010263.96  0.0718       0
#XS Ineff= 2 , 0
       0                10086.26       0
Bank Sta=9655.597,10263.96
Exp/Cntr=0.3,0.1

Type RM Length L Ch R = 1 ,15620.28,837.763400,837.763400,837.763400
XS GIS Cut Line= 6
784684.864945244827088.889822909784682.987290599826954.684146347
784695.533455922826871.611153436784762.861084461826710.447626778
784748.180102682826659.431511897 784647.90567134826449.437266867
#Sta/Elev= 30
9534.837272.69599558.793271.02269578.819261.18139588.821257.58179598.822254.9429
9628.826243.72229658.852235.75819678.909232.33569688.959232.01689750.392223.9935
9781.036221.3887 9802.45222.89049824.525222.48719835.825222.97289892.324219.6489
9924.344220.23179934.453219.81869954.915220.68079976.402220.39169998.548211.6634
 10009.8214.344110021.04224.321610032.29232.909710043.54240.514310054.79243.2911
10088.51243.059210110.62243.761910132.73245.984210176.66248.850410215.26252.8261
#Mann= 3 , 0 , 0
9534.837  0.0543       09534.837  0.0543       010215.26  0.0543       0
#XS Ineff= 2 , 0
       0                               0
Bank Sta=9534.837,10215.26
Exp/Cntr=0.3,0.1

Type RM Length L Ch R = 1 ,14782.52,230.225800,230.225800,230.225800
XS GIS Cut Line= 6
785246.393920462826916.644138523 785209.04077825826837.266416654
 785098.43427074826684.008859143785081.065960616826649.911965519
 785061.36414507 826576.60069482785006.945396543826480.396904841
#Sta/Elev= 30
9757.161247.20189780.407247.30259791.381246.77599824.773233.41729921.095233.4427
9938.348232.50289946.227230.10149958.793221.41569971.359215.83299983.925211.6023
9996.491209.310210000.65209.185810004.62209.289110008.77210.178910020.85215.8122
10032.94217.0295 10041.7218.723910055.47223.2521 10072.4232.654910088.07242.3526
10092.15245.446310098.58249.393710119.46249.729410129.66250.545710139.86250.0921
10173.25251.312410184.74252.378410230.69253.579510242.18254.556110258.96255.1135
#Mann= 3 , 0 , 0
9757.161  0.0501       09757.161  0.0501       010258.96  0.0501       0
#XS Ineff= 2 , 0
       09933.635                       0
Bank Sta=9757.161,10258.96
Exp/Cntr=0.3,0.1

Type RM Length L Ch R = 1 ,14552.29,292.289000,292.289000,292.289000
XS GIS Cut Line= 4
785431.424563169827057.219821513785405.382896513826799.407321498
785297.309979826826558.521904841785105.903729826826393.157321498
#Sta/Elev= 30
9511.581242.56989523.863242.73659543.965242.15939554.016241.33179564.067239.1817
9584.168238.03769594.219237.96989614.321246.30519634.423246.56029644.474246.1389
9664.576243.92779684.677 235.2819694.728234.65799704.779233.4729 9714.83232.8062
9874.179231.2722  9896.1 229.9179950.901229.31079961.861229.28469972.822229.7014
9983.782229.337310016.66 229.24810027.62228.906910055.41229.786510090.64231.9224
10116.59233.7653 10143.5236.630910162.48238.243210193.07240.202110287.67247.1965
#Mann= 3 , 0 , 0
9511.581    0.06       09511.581    0.06       010287.67    0.06       0
#XS Ineff= 2 , 0
       0 9926.13                       0
Bank Sta=9511.581,10287.67
Exp/Cntr=0.3,0.1

Type RM Length L Ch R = 1 ,   14260,253.983900,253.983900,253.983900
XS GIS Cut Line= 5
785502.284392763827049.013342361785542.152123155826840.876872714
785548.439278356826789.215034442785604.601646533826507.740654841
785595.100766964826130.080692677
#Sta/Elev= 30
9515.142235.34479600.683234.47539635.889237.14979671.955235.66079773.278235.1507
9854.783236.09119915.966232.7484 9936.36228.92549956.755217.72069997.543203.8093
10007.74208.235210017.94208.829510038.33 220.89410048.53221.985110058.73220.0627
10068.87213.839310098.88211.277710188.91213.378610208.91215.894810218.92219.8051
10228.92221.118110248.93 218.81610308.95216.487610328.95221.978810348.96230.6726
10368.96241.650710378.97243.808810398.97252.430710418.98  254.9510443.91263.8248
#Mann= 3 , 0 , 0
9515.142    0.06       09515.142    0.06       010443.91    0.06       0
#XS Ineff= 2 , 0
       0                10047.78       0
Bank Sta=9515.142,10443.91
Exp/Cntr=0.3,0.1

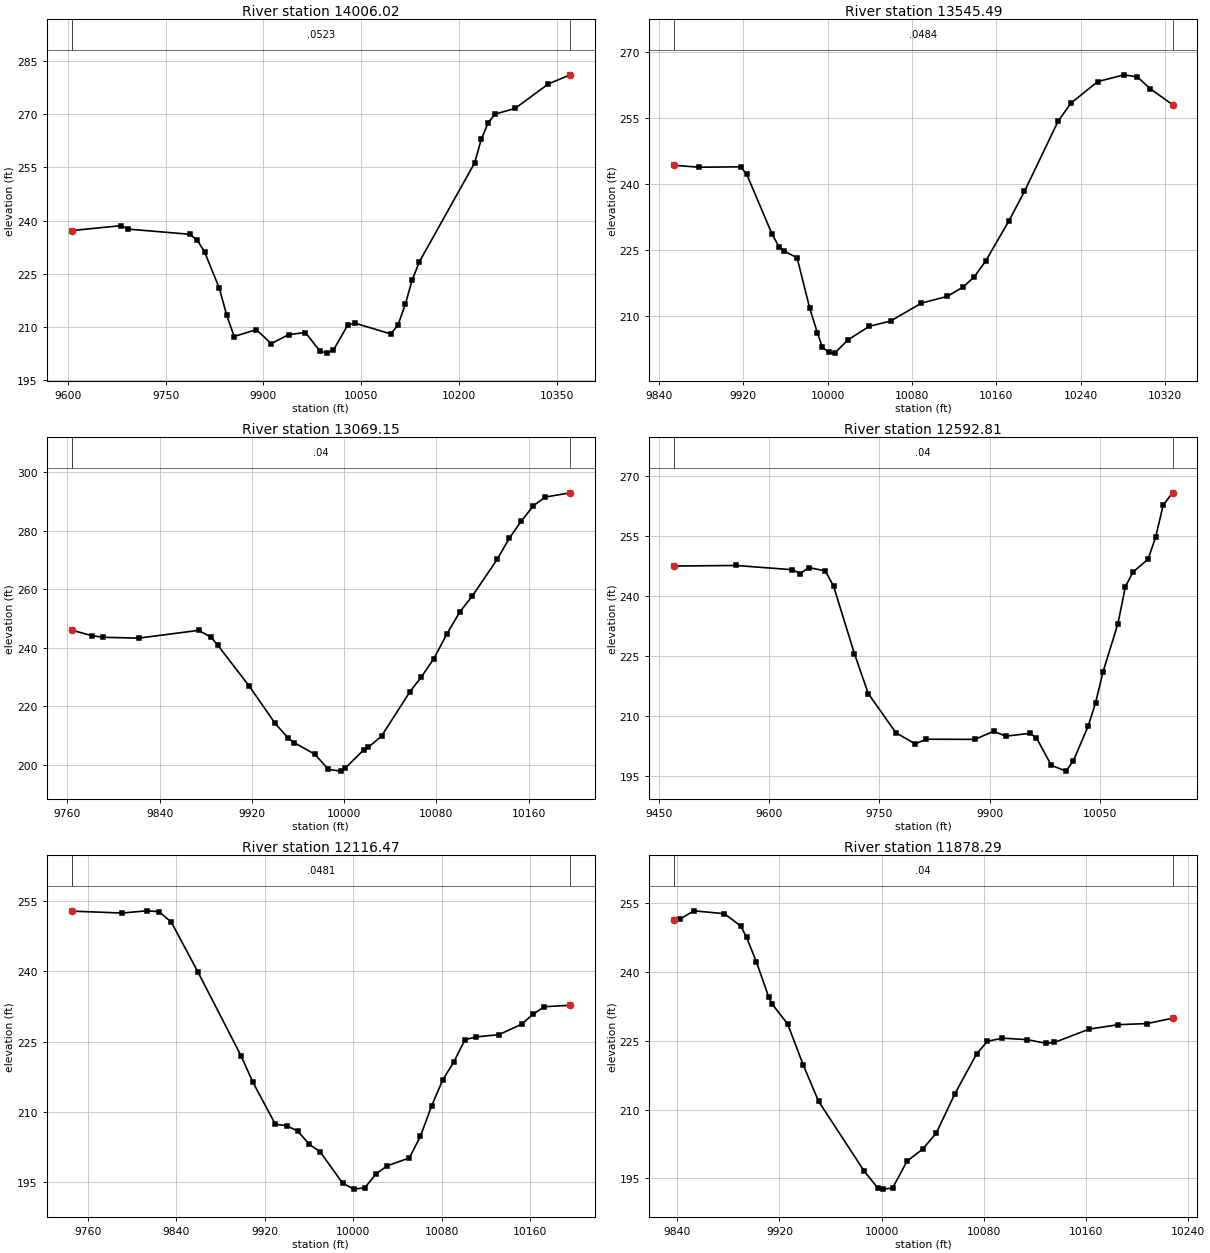
Type RM Length L Ch R = 1 ,14006.02,460.528700,460.528700,460.528700
XS GIS Cut Line= 6
785631.701066166826930.854906559785647.326066166826781.549350992
785817.758317787826690.188903472785826.746032084826673.258581182
785906.764767675826472.050857048785949.253952605826291.942635981
#Sta/Elev= 30
9605.577237.14729681.846238.56319691.901237.58129787.097236.11039798.443234.4772
9809.789231.08059832.482220.80759843.828213.19019855.174207.25049889.212209.1986
9911.905205.23129938.889207.77519964.517208.38229986.813 203.1279996.997202.5601
10007.57203.408310029.26210.409210040.32 211.02310095.65207.985810106.72210.5168
10117.85216.326410128.56 223.25610139.33228.292210224.25256.247810234.69263.0596
10245.12 267.60910255.56 270.03210286.37271.644210337.48278.556410370.91281.1328
#Mann= 3 , 0 , 0
9605.577  0.0523       09605.577  0.0523       010370.91  0.0523       0
#XS Ineff= 2 , 0
       0                 10029.5       0
Bank Sta=9605.577,10370.91
Exp/Cntr=0.3,0.1

Type RM Length L Ch R = 1 ,13545.49,476.341800,476.341800,476.341800
XS GIS Cut Line= 6
785733.558066509827154.501563094785755.378507418827114.347055486
785816.324100768827020.697237838785860.597957575826968.826851582
785905.165601239 826871.44339871785988.001522282826758.509489801
#Sta/Elev= 30
9854.209244.31229878.173243.87269917.416 243.9689923.067242.32229947.007228.7845
9953.807225.75229958.977224.75939970.947223.29799982.916211.85379990.198206.2191
9994.886202.9581   10001201.757310006.61201.588410019.34204.611510039.52 207.699
10059.77208.891510089.03212.968410113.39214.479110128.17216.566510138.97218.8849
10149.77222.469710171.97231.658510186.77238.384710218.75254.383210230.94258.4592
10256.13263.340710281.32264.891710293.91264.407810305.88261.758310327.27258.1025
#Mann= 3 , 0 , 0
9854.209  0.0484       09854.209  0.0484       010327.27  0.0484       0
#XS Ineff= 2 , 0
       0                               0
Bank Sta=9854.209,10327.27
Exp/Cntr=0.3,0.1

Type RM Length L Ch R = 1 ,13069.15,476.341800,476.341800,476.341800
XS GIS Cut Line= 6
786283.037731216827042.508201561786278.060144619826993.678635712
786262.223291297826936.891668187786236.395019491826880.661097488
786153.159744808826729.804050008 786128.54124154826643.677911482
#Sta/Elev= 30
9763.699245.98859781.266244.09159791.338 243.5329821.729243.2499 9873.88245.9078
9884.732243.52929890.422240.84339917.707226.88499940.258214.09869951.776209.0078
9956.703207.53689974.812203.5767 9986.33198.41719997.011197.8341   10001198.8613
10016.98205.069110020.96 205.972 10032.5209.8076 10057.2225.020810066.76229.8408
10077.94236.292210089.11244.679910100.29 252.16510111.25257.665210132.69270.1179
10143.34277.417210153.73283.230710164.13288.449510174.42291.4179   10196292.8689
#Mann= 3 , 0 , 0
9763.699    0.04       09763.699    0.04       0   10196    0.04       0
#XS Ineff= 2 , 0
       0                               0
Bank Sta=9763.699,10196
Exp/Cntr=0.3,0.1

Type RM Length L Ch R = 1 ,12592.81,476.341700,476.341700,476.341700
XS GIS Cut Line= 6
786353.086785795827043.313363097786415.945168809826892.493585397
786471.653393109826795.661897745786514.662980805826744.380002852
786622.511843111826653.373624802786651.419894924826462.752677672
#Sta/Elev= 30
9470.748247.51539555.149247.64959631.426246.59089642.542245.62299653.721247.1444
9676.456 246.2899687.688242.43289716.036225.54889734.794 215.5969772.203205.8537
9798.592203.02999813.458204.2068 9879.92204.16029905.105206.19989921.677204.9632
9954.466205.67679963.392204.5491 9983.49197.6974 10003.5196.223410013.51 198.797
10033.58207.4193 10043.7213.284310053.81221.023210074.03 233.02110084.28242.3578
10094.56245.995910115.12249.229210125.41254.748910135.69262.785110148.39265.8203
#Mann= 3 , 0 , 0
9470.748    0.04       09470.748    0.04       010148.39    0.04       0
#XS Ineff= 2 , 0
       09889.565                       0
Bank Sta=9470.748,10148.39
Exp/Cntr=0.3,0.1

Type RM Length L Ch R = 1 ,12116.47,238.170900,238.170900,238.170900
XS GIS Cut Line= 6
786410.665022739827093.372977316786460.792306004827055.224893392
 786532.64490232827026.237772937 786633.17435605827007.618658212
786747.471039288826994.957751067 786837.04042011826972.265911824
#Sta/Elev= 30
9745.233 252.8529790.719252.43999813.094252.91319824.255252.73319835.415250.4712
9859.306239.92139898.688221.83729908.938216.39959929.438207.34429939.608207.0601
9949.722205.88929959.835203.12489969.948201.46979990.166194.788810000.22193.5079
10010.28193.802610020.34196.730910030.41198.472210050.53200.1636 10060.6204.8069
10070.66211.268910080.72216.814410090.79220.660110100.85225.408810111.03226.0054
10131.48226.475210151.93228.699110162.15230.7971 10172.6232.443610195.88232.7534
#Mann= 3 , 0 , 0
9745.233  0.0481       09745.233  0.0481       010195.88  0.0481       0
#XS Ineff= 2 , 0
       0                               0
Bank Sta=9745.233,10195.88
Exp/Cntr=0.3,0.1

Type RM Length L Ch R = 1 ,11878.29,238.170900,238.170900,238.170900
XS GIS Cut Line= 6
786572.311542801827347.749917042786634.056442511827260.072684674
786672.788675654 827193.39482765786686.675571523827174.123226487
786719.053421463827147.146826961786841.585069689827079.822618308
#Sta/Elev= 30
9837.445251.33219842.114251.55699853.039 253.3539876.849252.72399889.731250.0324
9894.217 247.5569901.962242.18289911.585234.53019914.193233.03749926.424228.6471
9938.655219.68219950.565211.82039986.015196.70119996.962192.8822   10001192.6461
10008.47192.873510019.95198.776210032.14201.397410042.68204.846910057.14213.3602
10074.34 222.15610082.82224.903210094.54225.578310113.74225.254110128.49224.4757
 10135.1224.632110162.44227.549510185.08 228.51210207.83228.7662 10227.7229.9309
#Mann= 3 , 0 , 0
9837.445    0.04       09837.445    0.04       0 10227.7    0.04       0
#XS Ineff= 2 , 0
       0                               0
Bank Sta=9837.445,10227.7
Exp/Cntr=0.3,0.1

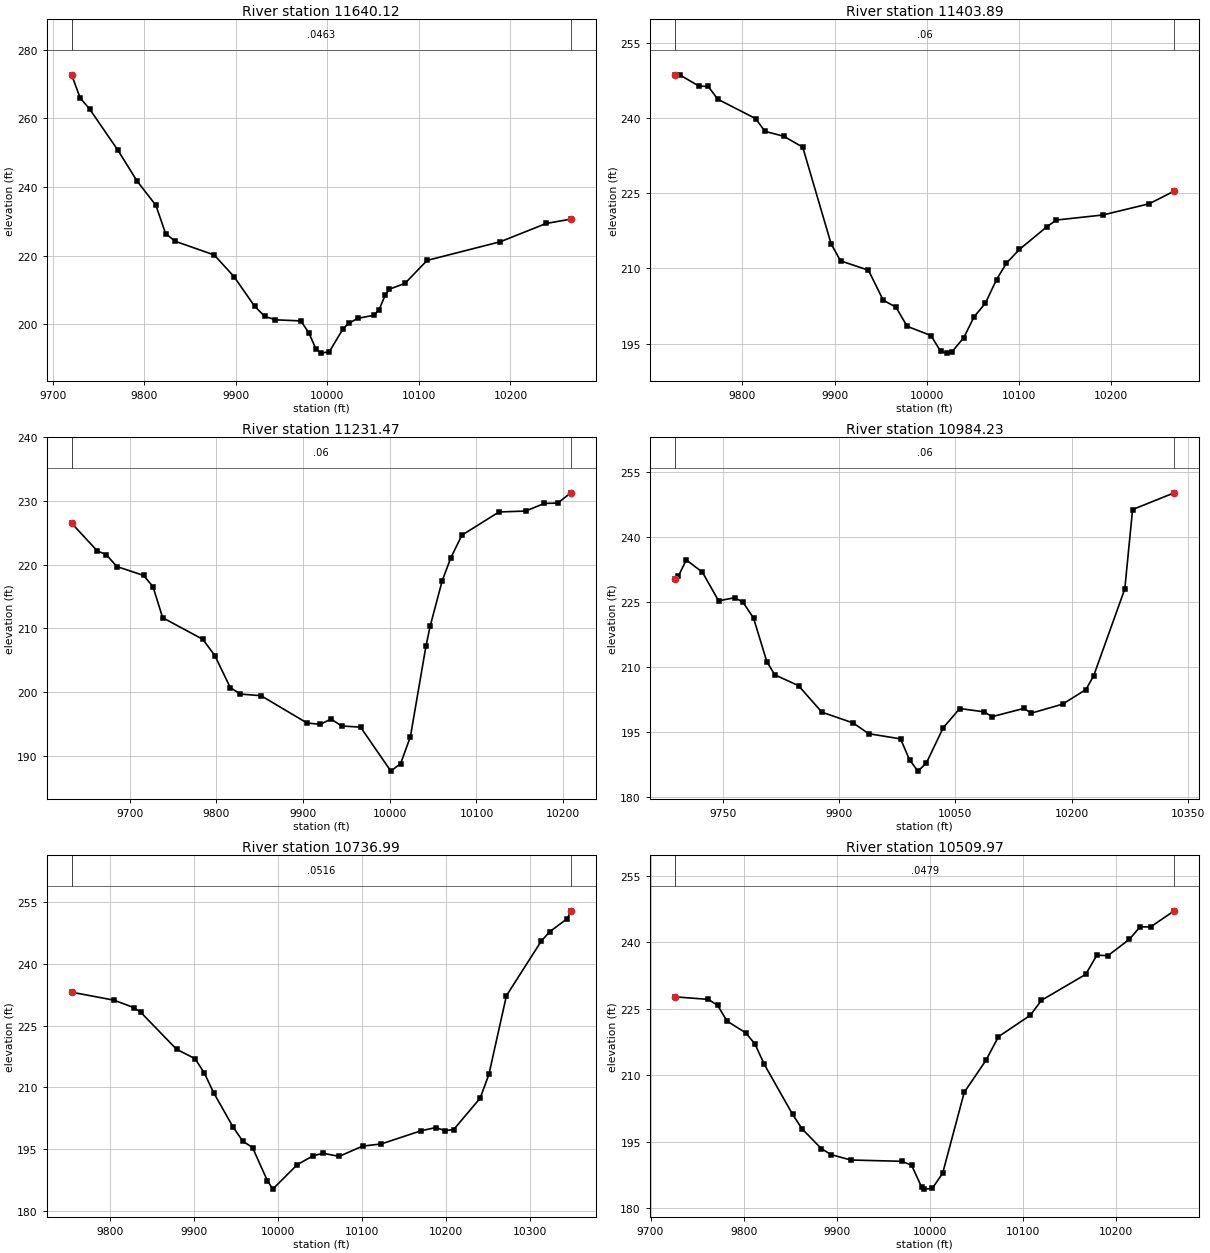
Type RM Length L Ch R = 1 ,11640.12,236.235500,236.235500,236.235500
XS GIS Cut Line= 6
786735.969426764827614.058524522786787.545361354827447.618667892
786820.901851937827387.143765703786873.255606842 827323.39260892
786888.319879595827288.862345488786888.634804379827108.133436417
#Sta/Elev= 30
9720.723272.67589730.009265.95859740.261262.73859771.195250.74169791.932241.8263
9812.785 234.6399823.326226.41989833.868224.1714 9876.49220.18379898.185213.8356
9920.542205.24679931.721202.28469943.368201.29419971.133200.97229979.697  197.52
9987.354192.9307 9992.81191.586410002.14191.981510017.01198.624510023.13200.2286
10033.05201.7083 10050.6202.602210056.57 204.29410063.21 208.48710067.66210.2072
10084.78211.907310108.94218.602610189.02224.049110239.07229.375410265.96230.6331
#Mann= 3 , 0 , 0
9720.723  0.0463       09720.723  0.0463       010265.96  0.0463       0
#XS Ineff= 2 , 0
       0                               0
Bank Sta=9720.723,10265.96
Exp/Cntr=0.3,0.1

Type RM Length L Ch R = 1 ,11403.89,172.421800,172.421800,172.421800
XS GIS Cut Line= 5
787138.455813199827570.240654841787099.393313169827391.855238155
          787055 827356.41409786786956.164146543827288.990654841
786937.934979856827108.001071498
#Sta/Elev= 30
9727.144248.61069732.509248.57979752.983246.3743 9763.22246.28669773.457243.7516
9814.405239.89819824.642237.34329845.116236.3562 9865.59234.1766  9896.3214.9168
9906.537211.51619936.772209.6506  9952.8203.65839966.562202.29659978.667198.4661
10004.56196.623710014.98193.461810022.31193.115510027.09 193.32910040.05 196.202
 10051.3200.3683 10063.4203.048310075.54207.7657 10086.2211.024810100.27213.7802
10130.42218.359110140.47 219.65510190.72220.661710240.97 222.89710268.11225.4292
#Mann= 3 , 0 , 0
9727.144    0.06       09727.144    0.06       010268.11    0.06       0
#XS Ineff= 2 , 0
       0                               0
Bank Sta=9727.144,10268.11
Exp/Cntr=0.3,0.1

Type RM Length L Ch R = 1 ,11231.47,247.238400,247.238400,247.238400
XS GIS Cut Line= 6
787312.391628882827472.775197657787209.028423578827258.322773657
787160.430179411827213.989657716787026.376755848827134.757580675
786995.051534682827097.594151934786976.252893548827034.903047122
#Sta/Elev= 30
9632.957226.52719662.395  222.199672.993221.57489685.174219.71319715.994218.3155
9726.793216.56049737.991211.67369784.369208.27269798.229205.70779815.949200.7026
9827.521199.67839851.512199.4201 9904.35195.14099919.658194.91069932.286195.7451
 9944.38194.65869966.286194.480210001.25187.565710012.52188.7525 10023.8192.9773
 10041.8207.260210046.53210.316510060.48217.480310070.46221.093310083.18224.6464
10126.04228.289410156.68228.433410178.36229.630210193.79229.693210208.93231.2986
#Mann= 3 , 0 , 0
9632.957    0.06       09632.957    0.06       010208.93    0.06       0
#XS Ineff= 2 , 0
       0                               0
Bank Sta=9632.957,10208.93
Exp/Cntr=0.3,0.1

Type RM Length L Ch R = 1 ,10984.23,247.238400,247.238400,247.238400
XS GIS Cut Line= 6
787332.862585223827459.033933437787295.051722071827317.595418504
787289.596653863827240.902120941787351.256456514827034.842943231
787355.566839029826957.391517287787346.036344423826831.561262034
#Sta/Elev= 30
9688.672230.39589692.868230.9627 9703.27234.77339724.072231.91939744.875225.3103
9765.678226.0317 9776.08225.04249789.942221.30989807.043211.22899817.292208.2117
9847.845205.68659878.081199.55699918.152197.0804 9938.39194.58229979.324193.3973
9990.937 188.54710001.74185.935710012.61187.810910034.34195.985510055.66200.4098
 10087.1199.638410097.32198.532910138.02200.422810148.06199.352810188.16201.4197
10218.17204.792310228.18207.972210268.28228.054310278.33246.417810331.99250.2829
#Mann= 3 , 0 , 0
9688.672    0.06       09688.672    0.06       010331.99    0.06       0
#XS Ineff= 2 , 0
       0                10068.15       0
Bank Sta=9688.672,10331.99
Exp/Cntr=0.3,0.1

Type RM Length L Ch R = 1 ,10736.99,227.021100,227.021100,227.021100
XS GIS Cut Line= 6
  787645.9537751827363.635323985787611.214632893827254.019133163
 787588.27440797827205.014151152787507.231459787827079.386498014
787475.976667775827018.916967907787413.026511824826820.842835252
#Sta/Elev= 30
9754.008233.11579804.409231.17869827.785229.39039836.233228.25489879.056 219.227
9901.139216.9415 9912.18213.42869923.206208.69279946.407200.30969957.999196.8671
9969.591195.32449987.201 187.3059993.715185.212910022.87191.168810041.95193.3418
10053.98193.932210072.77 193.17510100.71195.674510123.05196.209710170.34199.4066
10188.18200.196810198.76199.434610209.33199.706110240.85207.346410251.28213.1358
10272.14232.2512 10313.7245.551410324.02247.869810344.66250.994810348.95252.9063
#Mann= 3 , 0 , 0
9754.008  0.0516       09754.008  0.0516       010348.95  0.0516       0
#XS Ineff= 2 , 0
       0                10053.07       0
Bank Sta=9754.008,10348.95
Exp/Cntr=0.3,0.1

Type RM Length L Ch R = 1 ,10509.97,267.455800,267.455800,267.455800
XS GIS Cut Line= 6
787784.042625308827260.853282086787776.717261592827151.916904481
787751.445642473827061.109263735787715.956650794 826984.77026325
787617.086274994826828.930214466787586.388933758826772.737870676
#Sta/Elev= 30
9726.282227.71059762.183227.13379772.196225.76169782.209222.23889802.236219.5944
9812.281217.0483 9822.34212.4383 9852.73201.15979862.916197.89499883.522193.4542
9893.958192.10269915.141190.87199970.171190.57489980.541189.69099991.528184.6762
9994.191184.296710002.74184.451110013.95187.878310037.14206.152510060.47213.3824
10073.94218.718410108.14223.550410120.05226.915510167.72 232.78910179.64237.1097
10191.56237.005910214.67240.699810226.06243.509410237.46243.504910262.82247.1298
#Mann= 3 , 0 , 0
9726.282  0.0479       09726.282  0.0479       010262.82  0.0479       0
#XS Ineff= 2 , 0
       0                               0
Bank Sta=9726.282,10262.82
Exp/Cntr=0.3,0.1

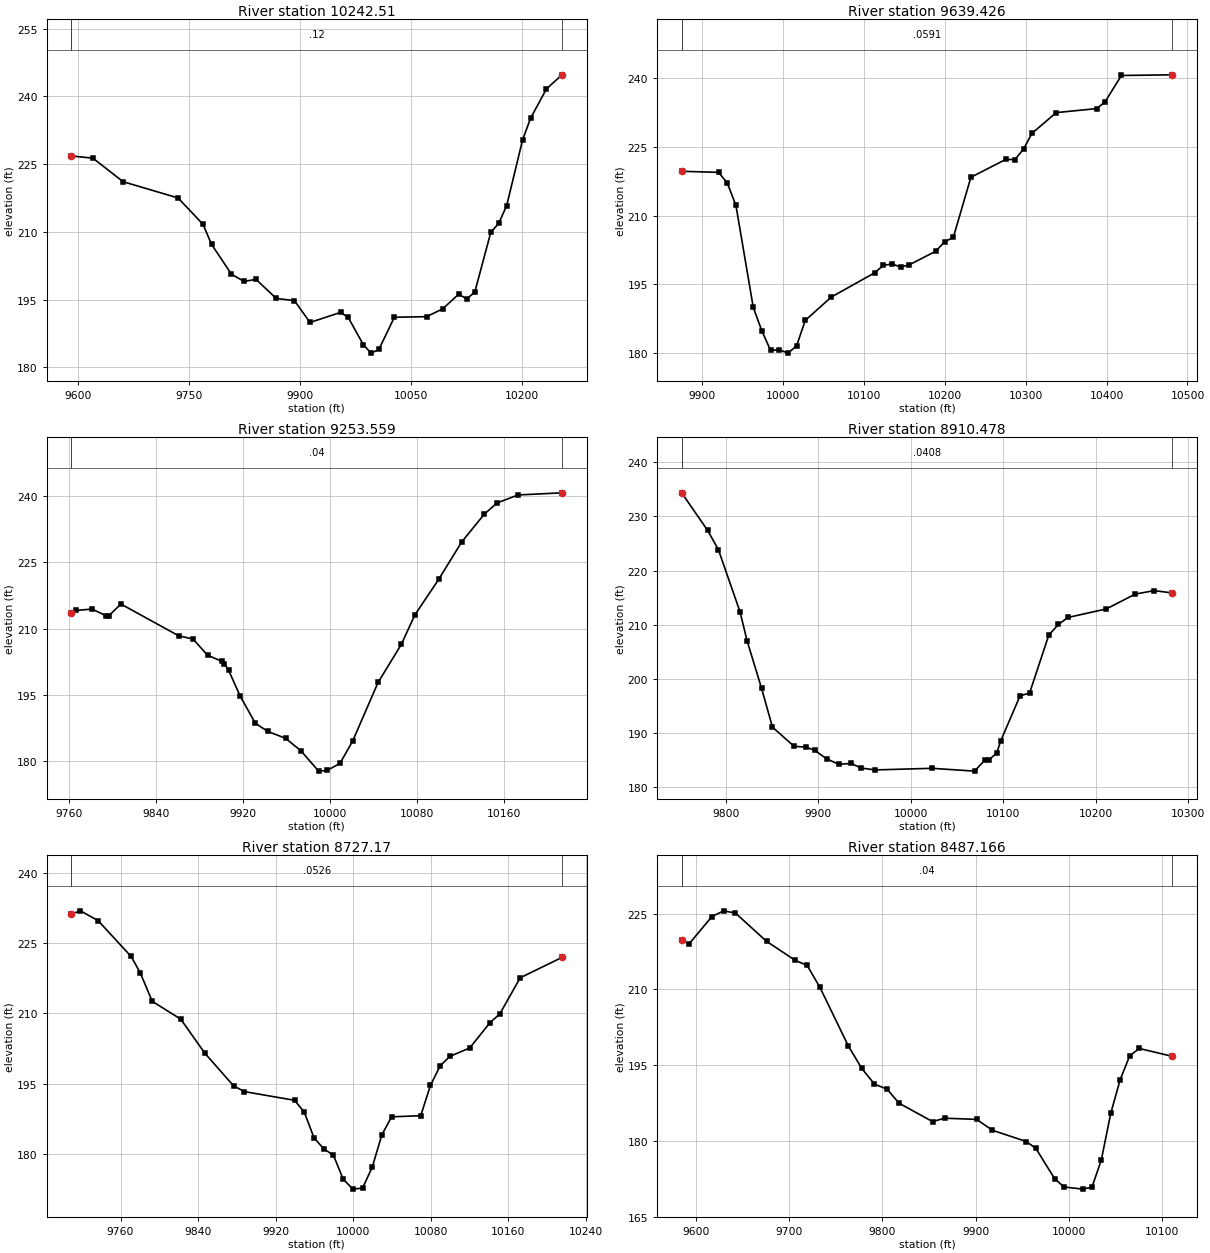
Type RM Length L Ch R = 1 ,10242.51,603.086200,603.086200,603.086200
XS GIS Cut Line= 6
787833.450362428827224.078205032787844.800087188827156.853915094
787875.191164644827072.212243411787963.059196767826936.722446892
787935.771715561826827.293006592787848.923337623826615.360593689
#Sta/Elev= 30
9591.291226.81679620.638226.32939661.448221.10689735.696 217.5149769.389211.6686
9780.895207.24859807.774200.63819824.817199.02119841.046199.47639868.247195.2621
9893.007194.75919913.982189.93029955.192192.14769965.458 191.088 9986.26184.9391
9996.661183.135510007.03183.943410027.95191.080610071.43191.214110093.16192.9228
 10114.9196.197610125.77195.145510136.64196.646710158.27209.887610169.02211.8957
10179.77215.827310201.26230.390510212.01235.151710233.51241.679710254.52244.7911
#Mann= 3 , 0 , 0
9591.291    0.12       09591.291    0.12       010254.52    0.12       0
#XS Ineff= 2 , 0
       0                               0
Bank Sta=9591.291,10254.52
Exp/Cntr=0.3,0.1

Type RM Length L Ch R = 1 ,9639.426,385.867400,385.867400,385.867400
XS GIS Cut Line= 5
788053.576066166827267.660462096788145.589955062827028.077128768
  788211.5621773826871.827128768788204.617732882826783.285462111
788187.748733644826692.915823435
#Sta/Elev= 30
9874.437219.64459920.136219.40859930.848217.0882 9941.56212.18349962.984189.9529
9973.696184.78629984.409 180.5799995.121180.721710005.83 179.98510016.54181.5635
10027.26187.117610059.39192.201510112.95197.493310123.67199.097210134.42199.4512
10145.28198.762910156.13199.2587 10188.7 202.21210199.55204.251710210.41205.2413
10232.12218.336910275.54222.259110286.39222.172110297.24224.489810307.54 227.905
10337.63232.440210387.78233.323210397.93234.758410418.28240.539510481.43240.6835
#Mann= 3 , 0 , 0
9874.437  0.0591       09874.437  0.0591       010481.43  0.0591       0
#XS Ineff= 2 , 0
       0                               0
Bank Sta=9874.437,10481.43
Exp/Cntr=0.3,0.1

Type RM Length L Ch R = 1 ,9253.559,343.081000,343.081000,343.081000
XS GIS Cut Line= 6
788529.450617406 827067.89572283788420.393941614826972.504623471
788359.071547627826903.560261356788327.134340308826851.230721259
788308.489722357826809.458304641788280.800010557826705.673309932
#Sta/Elev= 30
9761.693213.57889766.091214.12429780.892214.40899794.177212.86999796.469212.9454
9807.463215.55769860.606208.36279873.891207.62339887.177203.95959900.463202.5752
9902.792 201.9919906.582200.55329917.143194.73759931.216188.53049942.674186.6667
9958.979185.13219973.257182.26999989.419177.67729997.167177.834810009.09179.4154
10020.79184.498110044.19197.784710065.54 206.38810078.08 213.09710099.98221.1509
 10121.2229.641510142.14235.989710153.83 238.48610173.03240.293310213.52240.7766
#Mann= 3 , 0 , 0
9761.693    0.04       09761.693    0.04       010213.52    0.04       0
#XS Ineff= 2 , 0
       0                               0
Bank Sta=9761.693,10213.52
Exp/Cntr=0.3,0.1

Type RM Length L Ch R = 1 ,8910.478,183.307400,183.307400,183.307400
XS GIS Cut Line= 4
788748.955339725826791.713192699788633.701236183826721.834720505
788499.389367456826565.742548762788316.071816946826514.921841709
#Sta/Elev= 30
9752.037234.36879780.052227.44579791.746 223.8829815.135 212.4119822.851207.0144
9838.524198.24429850.218191.10999873.607187.56689886.821187.40359895.837186.8384
 9909.03185.23169922.222184.24479935.414184.40239946.156183.55489961.488183.2064
10022.81183.503510068.81182.983610080.53185.112210084.14185.028310092.74186.2978
 10097.3188.617310118.05196.873510128.43197.411310149.18208.101710159.56210.0707
10169.94211.355710211.45212.932810242.58215.666810263.33216.314810282.98215.8722
#Mann= 3 , 0 , 0
9752.037  0.0408       09752.037  0.0408       010282.98  0.0408       0
#XS Ineff= 2 , 0
       09928.532                       0
Bank Sta=9752.037,10282.98
Exp/Cntr=0.3,0.1

Type RM Length L Ch R = 1 , 8727.17,240.003800,240.003800,240.003800
XS GIS Cut Line= 6
788802.707543343826571.244522483788691.005822723826490.427081439
 788638.60628792826465.194870359788464.072924577826454.652719826
788377.447848968826434.955207738788335.608216211826416.282864313
#Sta/Elev= 30
9709.087231.1648  9718.6231.8521  9736.8229.76499770.919222.11729780.315218.6406
9792.658 212.5629822.098208.75869846.959201.49969876.569194.54699887.779193.3142
9939.515191.4554 9949.56188.92339959.604183.45579969.607181.11699979.607179.7542
9989.607174.66549999.607172.522110009.61172.727410019.61177.179310029.61184.1199
10039.62187.933910069.68188.1764 10079.7194.629410089.83198.853310099.97200.8405
10120.26202.620910140.89207.943910151.32209.896610172.29217.575210215.43221.9238
#Mann= 3 , 0 , 0
9709.087  0.0526       09709.087  0.0526       010215.43  0.0526       0
#XS Ineff= 2 , 0
       0                               0
Bank Sta=9709.087,10215.43
Exp/Cntr=0.3,0.1

Type RM Length L Ch R = 1 ,8487.166,249.866500,249.866500,249.866500
XS GIS Cut Line= 6
788861.386906435826567.604433249788715.833355816 826448.49804118
788654.934417701826370.844256195788624.326545971826299.134701471
788615.416808216826195.081032386788599.646130229 826141.25448417
#Sta/Elev= 30
9584.708 219.7979592.567219.01469617.178224.44399629.739225.57539642.378225.1352
9675.683219.5362 9706.54215.76129719.251214.76169732.981210.41269763.489198.7899
9777.777194.37399791.466191.25159805.033190.2406 9817.94187.45559853.717183.8352
9866.929184.49759900.966184.26259917.978182.10929954.282179.88219964.522178.5269
9984.684172.51229994.686170.880710014.71170.448110024.71170.835110034.77176.2382
10044.88 185.46610054.91 192.09410065.28196.891810075.56198.305210111.07196.7445
#Mann= 3 , 0 , 0
9584.708    0.04       09584.708    0.04       010111.07    0.04       0
#XS Ineff= 2 , 0
       0 9940.45                       0
Bank Sta=9584.708,10111.07
Exp/Cntr=0.3,0.1