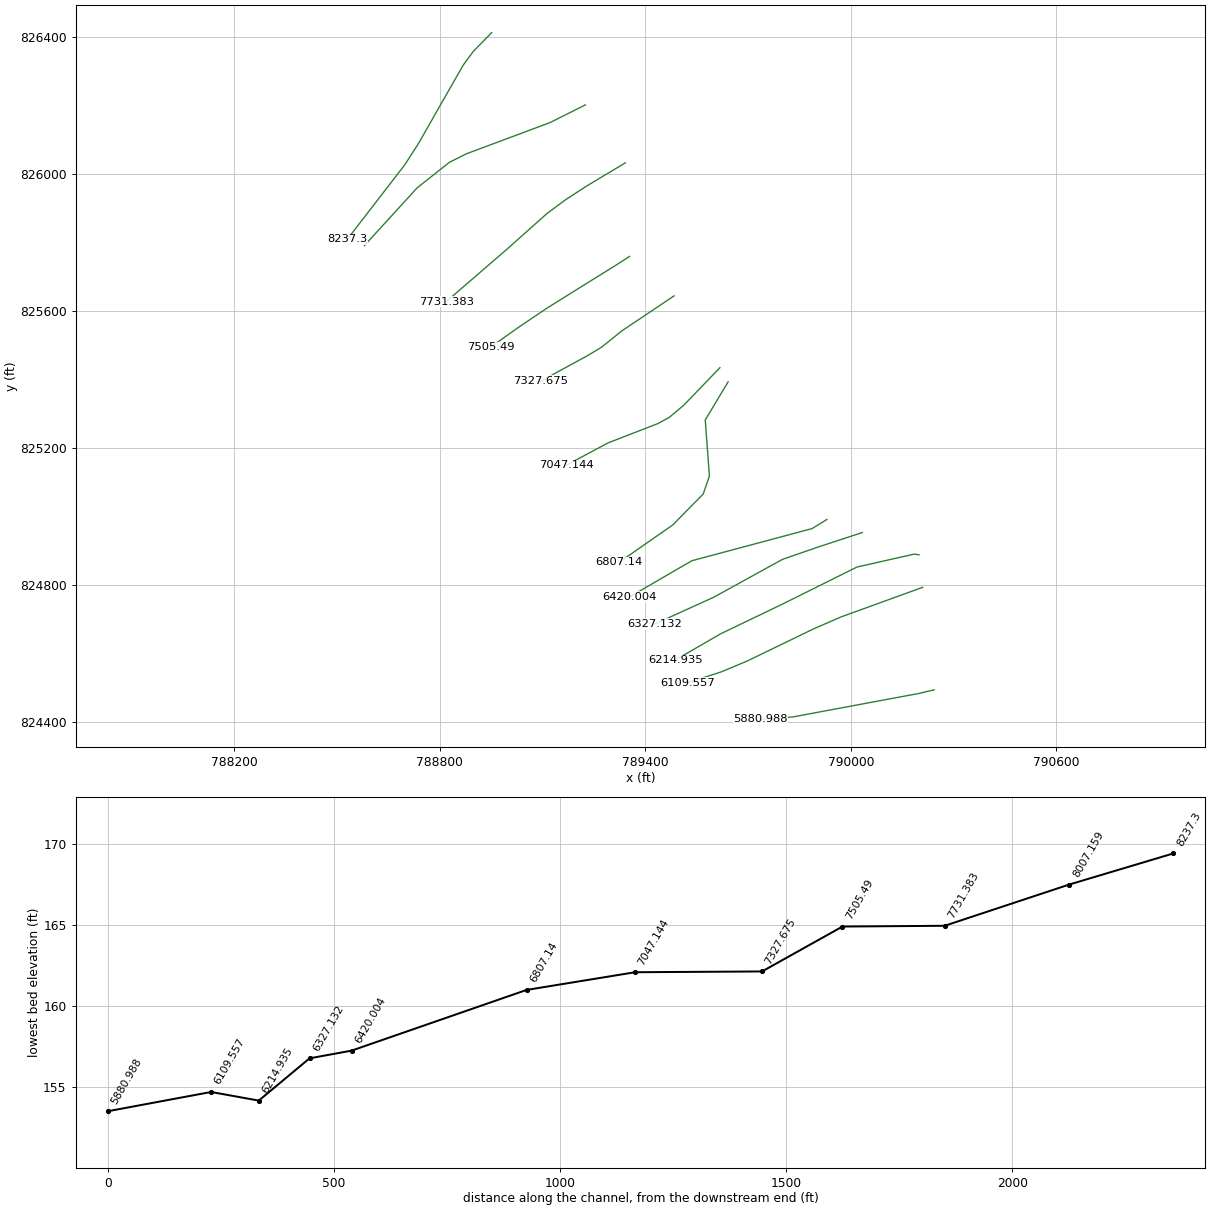
HEC-RAS study 18178_ras.prj: 18178

--- 18178_ras.g01 (geometry) --- (continued)

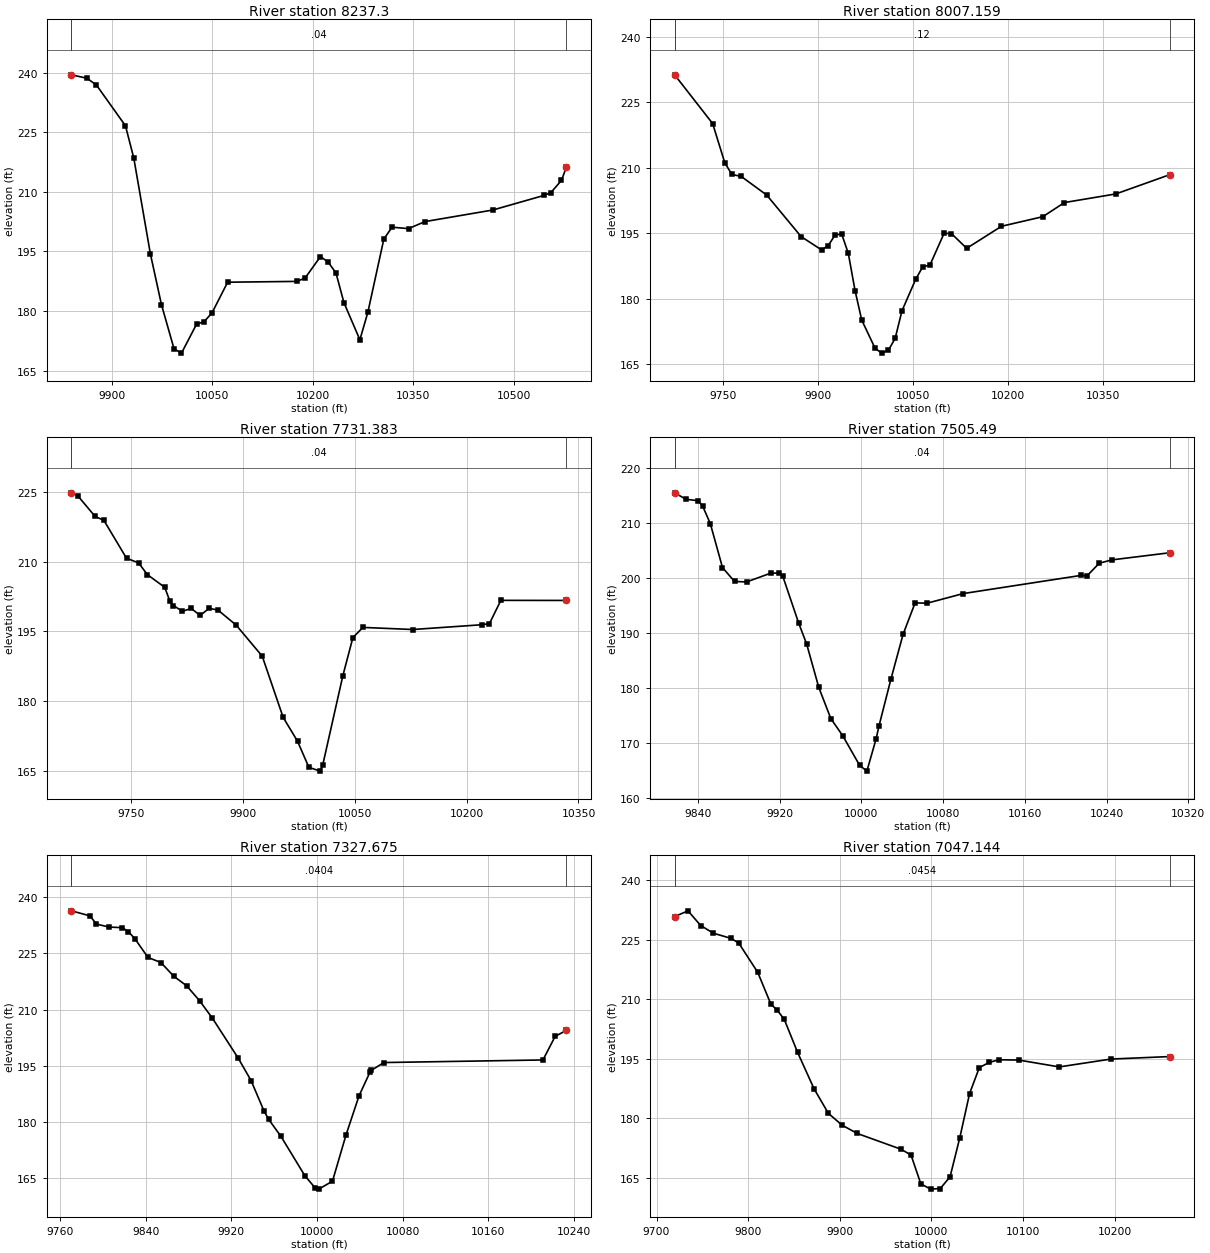
Type RM Length L Ch R = 1 ,  8237.3,230.141100,230.141100,230.141100
XS GIS Cut Line= 6
788952.170888452826413.002473862788898.211925436826357.708137639
 788868.93371746 826317.89051785788737.736333548826088.021500352
788697.688027477  826026.0670218 788530.36276946825809.267384944
#Sta/Elev= 30
9839.419239.45129862.601238.59499876.855236.86889920.128226.6336 9932.54 218.549
9957.365194.40029973.903181.62029992.734170.478610003.83169.416610026.29176.6895
 10037.7177.353910049.39179.533310072.76 187.26310175.89187.4676 10188.4188.2954
10211.42193.719810222.93192.318410234.56189.593910246.46182.111410270.28172.7759
10282.18179.694910306.04198.116910318.33 201.10910342.92200.7481 10367.5202.5178
 10468.9205.434910545.44209.111710555.52209.810810571.33212.880410578.66216.2087
#Mann= 3 , 0 , 0
9839.419    0.04       09839.419    0.04       010578.66    0.04       0
#XS Ineff= 2 , 0
       0                10074.59       0
Bank Sta=9839.419,10578.66
Exp/Cntr=0.3,0.1

Type RM Length L Ch R = 1 ,8007.159,275.775400,275.775400,275.775400
XS GIS Cut Line= 6
789225.577233806826202.001147792789122.269252512826150.322134945
788878.764241779826059.461566328788828.656991279826034.371337613
788734.613522626825959.972775117788580.866275039 825791.55423006
#Sta/Elev= 30
9674.436231.25459734.395220.07699753.425211.11279764.586208.44859779.425207.9726
 9819.52203.71269873.726 194.1979905.949191.14999916.495192.12379927.041194.5319
9937.587194.81059948.133190.33129958.679181.84719969.225175.08319990.317168.5973
10000.84   167.510011.34168.175410021.91170.872510032.63177.183710054.24184.4058
10065.42187.303310076.61187.639710098.97194.938910110.48194.903910134.63191.5076
10189.42196.560710254.49198.752510288.73201.999110369.57203.965910454.32208.3652
#Mann= 3 , 0 , 0
9674.436    0.12       09674.436    0.12       010454.32    0.12       0
#XS Ineff= 2 , 0
       0                10103.06       0
Bank Sta=9674.436,10454.32
Exp/Cntr=0.3,0.1

Type RM Length L Ch R = 1 ,7731.383,225.893300,225.893300,225.893300
XS GIS Cut Line= 6
789342.320806138826033.005591637789228.494159635825964.772866444
789167.268595318825924.918995841789113.243460259825884.803172457
788996.150038899825780.411558346788819.000290578825627.636676036
#Sta/Elev= 30
9669.885224.8034 9678.42224.16779701.739219.71279713.398218.89619743.805 210.734
9760.034209.73589771.693207.21949795.011204.49029802.154201.43999806.765 200.559
9818.697199.33669830.629199.93269842.561198.43639854.493199.95759866.425199.6013
9890.931196.34339925.836189.67329953.859176.52319973.139171.39649988.389165.7749
10003.59164.955810006.94166.247810033.92185.440310047.41193.6645 10060.9195.8624
10127.75195.410210220.18196.4336 10230.6196.684610245.91201.678710333.75201.6613
#Mann= 3 , 0 , 0
9669.885    0.04       09669.885    0.04       010333.75    0.04       0
#XS Ineff= 2 , 0
       0                               0
Bank Sta=9669.885,10333.75
Exp/Cntr=0.3,0.1

Type RM Length L Ch R = 1 , 7505.49,177.815600,177.815600,177.815600
XS GIS Cut Line= 6
789354.335745392 825759.87672317789318.257762071825736.471843845
789199.321575513825662.515932829789110.211880081825606.774362662
789027.589870124825550.935151657 788948.98648874825494.903628202
#Sta/Elev= 30
9817.289215.51639828.417214.34549840.337 214.0839844.624213.14479852.257209.8907
 9864.13201.91999875.908 199.4029887.685199.31149911.239 200.9029919.873200.9389
9923.016200.41829938.804191.76759946.571187.98129958.348180.14669970.125174.4735
9981.902171.32099998.348  165.9610005.45164.908910014.52170.810410017.24173.0877
10029.04181.684410040.83189.762510052.63195.502610064.42195.447210099.81197.1992
 10215.4200.511210220.64200.367810232.92202.7212 10245.2 203.32110301.71204.6168
#Mann= 3 , 0 , 0
9817.289    0.04       09817.289    0.04       010301.71    0.04       0
#XS Ineff= 2 , 0
       0                               0
Bank Sta=9817.289,10301.71
Exp/Cntr=0.3,0.1

Type RM Length L Ch R = 1 ,7327.675,280.530800,280.530800,280.530800
XS GIS Cut Line= 6
 789484.38773016825644.687807362 789331.36288375825542.162102612
789295.282596115825512.914601965789271.443332362 825494.06964426
789229.987406272825469.266511964789095.815438822825396.141852035
#Sta/Elev= 30
9770.625236.35299787.898235.01479794.021232.80759805.878232.02229818.086231.8641
9823.858230.80069830.119228.82159842.152223.91369854.184222.57089866.217218.9048
 9878.25 216.3569890.283212.38189902.315207.70469926.381197.06219938.413191.0731
9950.446182.98569954.822180.73559966.262176.21499988.631165.70389998.207162.4631
10001.64 162.14110014.39164.263110027.13176.670910039.18187.009110049.33193.2888
10050.83193.852210062.48195.896310210.93196.585810222.32202.872810232.78204.4746
#Mann= 3 , 0 , 0
9770.625  0.0404       09770.625  0.0404       010232.78  0.0404       0
#XS Ineff= 2 , 0
       0                               0
Bank Sta=9770.625,10232.78
Exp/Cntr=0.3,0.1

Type RM Length L Ch R = 1 ,7047.144,240.003800,240.003800,240.003800
XS GIS Cut Line= 6
789618.124376329825435.103009285789512.557285838825325.573701076
 789470.17593194825290.030815491 789436.56764606 825271.76568631
789292.017073546825215.829765809789169.081005012 825150.12824521
#Sta/Elev= 30
9719.759230.80049734.358232.25199748.191228.54919762.024226.60959781.522225.2902
 9789.69224.13779810.468216.74979824.941208.65589831.189207.36819839.414204.8983
9853.886196.61629871.895187.41149887.585181.19289902.424178.23789918.978 176.135
9967.192172.12199977.846170.66119988.499163.42599999.151162.093110009.77162.2507
10020.41165.203410031.06175.0749 10041.7186.174910052.34192.722810062.99194.0297
10073.63194.703510095.43194.6301 10139.6192.901710195.98 194.88310260.03195.5101
#Mann= 3 , 0 , 0
9719.759  0.0454       09719.759  0.0454       010260.03  0.0454       0
#XS Ineff= 2 , 0
       0                               0
Bank Sta=9719.759,10260.03
Exp/Cntr=0.3,0.1

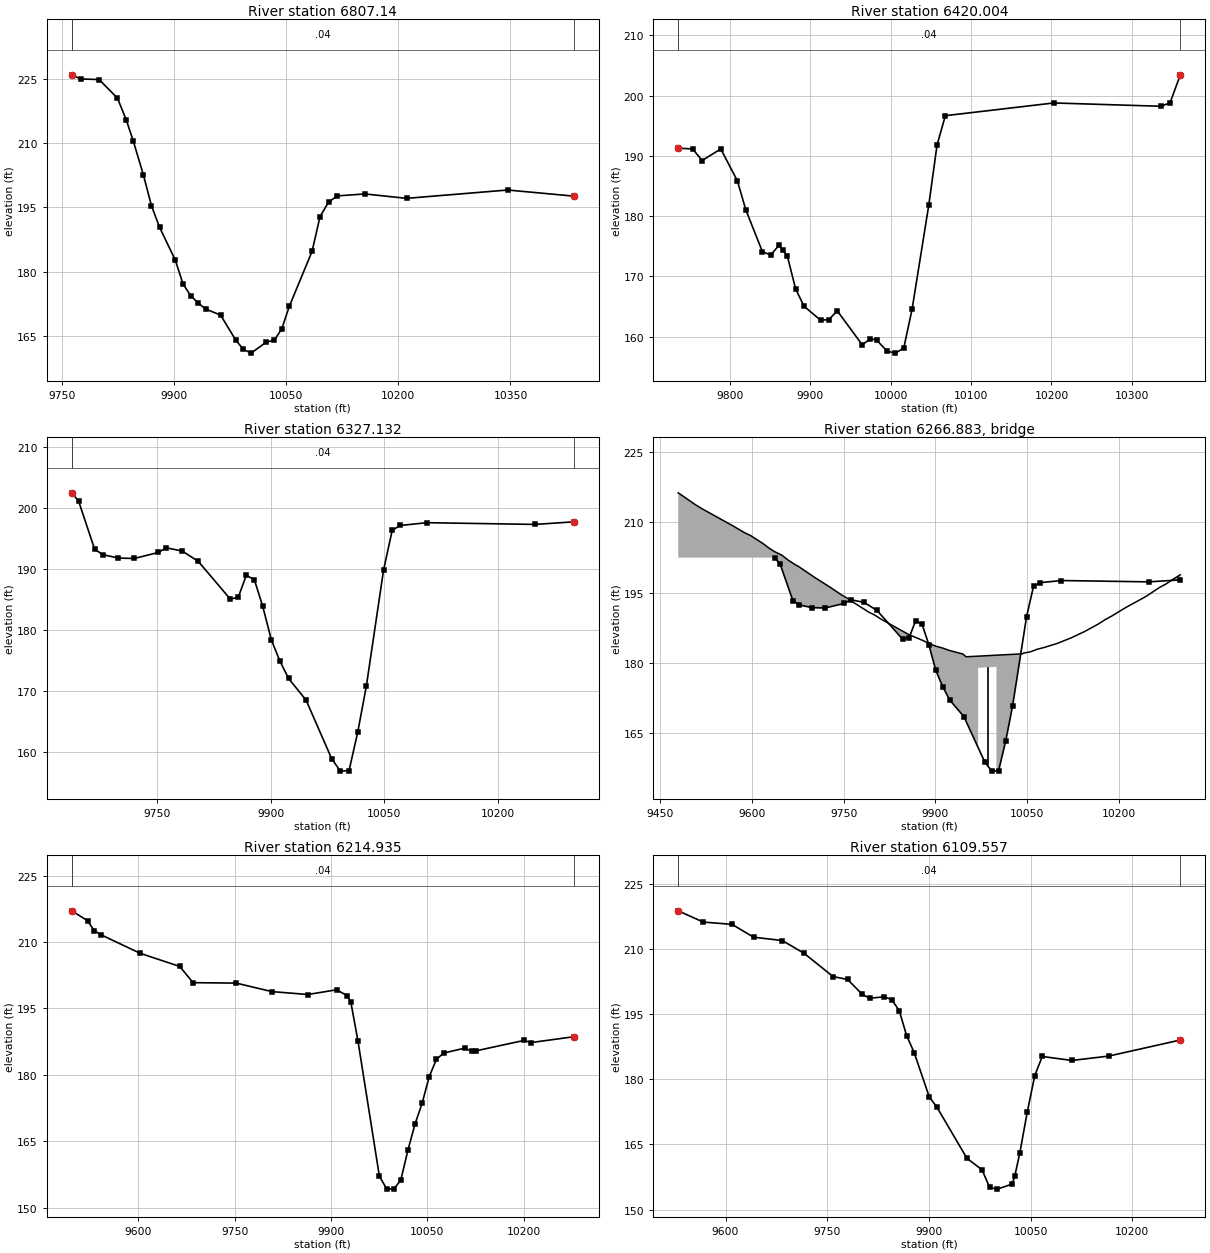
Type RM Length L Ch R = 1 , 6807.14,387.136000,387.136000,387.136000
XS GIS Cut Line= 6
789642.051280658825393.907121824789575.334029539825282.524055128
789587.495858381825119.041441554789569.448891307825066.677374036
789480.275785921824976.068333368789323.826555486824867.176692042
#Sta/Elev= 30
9763.591225.86559775.302224.90559800.162224.76669824.709220.41849836.217215.4529
 9845.94210.36889859.231202.59359870.111195.35549880.857 190.3659901.941182.6881
9912.143177.20499922.344174.41429932.444172.70359942.445171.27959962.526169.8697
9982.769164.02919993.022161.878610003.28161.002510023.84163.603910034.13163.9762
10044.26166.648410054.31171.884410084.77184.714510095.39  192.8110106.88196.2137
10118.67197.649410155.27198.105810211.07197.075710346.32199.0189 10434.7197.5939
#Mann= 3 , 0 , 0
9763.591    0.04       09763.591    0.04       0 10434.7    0.04       0
#XS Ineff= 2 , 0
       0                               0
Bank Sta=9763.591,10434.7
Exp/Cntr=0.3,0.1

Type RM Length L Ch R = 1 ,6420.004,92.871600,92.871600,92.871600
XS GIS Cut Line= 4
789930.337680388824992.219506845789886.909399509824965.577128768
789536.214955091824871.827128768789353.923288435824765.924351007
#Sta/Elev= 30
9735.575191.29979753.568191.1556  9765.3189.2426  9788.5191.16089809.203185.8634
9819.554181.09449840.256174.12289850.607173.54539860.958175.16939866.201174.3132
 9871.31173.38329881.661167.92319892.012165.05749912.714162.72489923.065162.8229
9933.416164.2918 9964.47158.65199974.821159.62449982.363159.44049995.523157.5817
10005.87157.259910016.23158.104110026.58164.557610047.28181.779110057.63191.8163
10067.98196.687110202.94198.797710335.98198.248110347.54198.806310360.35203.4684
#Mann= 3 , 0 , 0
9735.575    0.04       09735.575    0.04       010360.35    0.04       0
#XS Ineff= 2 , 0
       09929.877                       0
Bank Sta=9735.575,10360.35
Exp/Cntr=0.3,0.1

Type RM Length L Ch R = 1 ,6327.132,112.197400,112.197400,112.197400
XS GIS Cut Line= 5
790033.637526865824954.128923916789903.313607693824911.366387919
789800.728608519824875.817130789789599.621382385824765.106587127
789428.271833952824687.220428721
#Sta/Elev= 30
9637.086202.47379646.177201.09649667.226193.24269677.751192.3389  9698.8191.7644
9719.849191.69549751.423192.68579761.947 193.4469783.045192.91699804.212191.2267
9846.546 185.0299857.129185.33759867.712188.92129878.296188.23249889.356183.8782
9900.771178.35049912.186174.83419923.601171.99589946.718168.44679980.677158.7942
9992.092156.785710003.51156.873210014.92163.140210026.34170.709210049.17189.8182
10060.58196.333810071.13197.113310106.24197.570610249.27197.2875 10300.6197.7119
#Mann= 3 , 0 , 0
9637.086    0.04       09637.086    0.04       0 10300.6    0.04       0
#XS Ineff= 2 , 0
       0                               0
Bank Sta=9637.086,10300.6
Exp/Cntr=0.3,0.1

Type RM Length L Ch R = 3 ,6266.883,,,
BEGIN DESCRIPTION:
END DESCRIPTION:
Bridge Culvert--1,0,-1,-1, 0
Deck Dist Width WeirC Skew NumUp NumDn MinLoCord MaxHiCord MaxSubmerge Is_Ogee
43.598700,25.000000,2.6,0, 50, 47, , , 0.95, 0, 0,0,,
 9479.64 9508.06 9518.10 9568.30 9588.39 9598.43 9618.51 9628.55 9636.93 9648.78
 9660.28 9671.06 9675.54 9703.40 9729.06 9746.52 9757.31 9762.47 9790.33 9801.38
 9812.43 9856.64 9878.75 9889.80 9900.85 9911.90 9922.95 9945.04 9950.24 9970.00
 9970.0010000.0010000.0010042.1310044.3610055.4010066.4710077.5910099.8110122.03
10144.2610166.4810177.4210188.7010210.9310244.2610266.4910277.6010288.7110300.56
  216.34  213.77  212.97  209.33  207.79  207.16  205.46  204.47  203.77  203.02
  201.86  200.95  200.65  198.18  196.05  194.50  193.69  193.20  190.88  190.14
  189.22  186.01  184.79  184.09  183.52  183.13  182.61  181.85  181.26  181.39
  181.39  181.60  181.60  181.88  182.04  182.31  182.86  183.23  184.13  185.30
  186.67  188.26  189.18  189.99  191.76  194.15  196.08  196.86  197.85  198.80
 -783.66 -786.23 -787.03 -790.67 -792.21 -792.84 -794.54 -795.53 -796.23 -796.98
 -798.14 -799.05 -799.35 -801.82 -803.95 -805.50 -806.31 -806.80 -809.12 -809.86
 -810.78 -813.99 -815.21 -815.91 -816.48 -816.87 -817.39 -818.15 -818.74 -818.61
  178.89  179.10 -818.40 -818.12 -817.96 -817.69 -817.14 -816.77 -815.87 -814.70
 -813.33 -811.74 -810.82 -810.01 -808.24 -805.85 -803.92 -803.14 -802.15 -801.20
 9479.64 9508.06 9518.10 9568.30 9588.39 9598.43 9618.51 9628.55 9636.93 9648.78
 9660.28 9671.06 9675.54 9703.40 9729.06 9746.52 9757.31 9762.47 9790.33 9801.38
 9812.43 9856.64 9878.75 9889.80 9900.85 9911.90 9922.95 9945.04 9950.24 9982.10
 9982.1010012.1010012.1010042.1310044.3610055.4010066.4710077.5910099.8110131.55
10155.3710210.9310244.2610266.4910277.6010288.7110300.56
  216.34  213.77  212.97  209.33  207.79  207.16  205.46  204.47  203.77  203.02
  201.86  200.95  200.65  198.18  196.05  194.50  193.69  193.20  190.88  190.14
  189.22  186.01  184.79  184.09  183.52  183.13  182.61  181.85  181.26  181.47
  181.47  181.68  181.68  181.88  182.04  182.31  182.86  183.23  184.13  185.85
  187.42  191.76  194.15  196.08  196.86  197.85  198.80
 -783.66 -786.23 -787.03 -790.67 -792.21 -792.84 -794.54 -795.53 -796.23 -796.98
 -798.14 -799.05 -799.35 -801.82 -803.95 -805.50 -806.31 -806.80 -809.12 -809.86
 -810.78 -813.99 -815.21 -815.91 -816.48 -816.87 -817.39 -818.15 -818.74 -818.53
  178.97  179.18 -818.32 -818.12 -817.96 -817.69 -817.14 -816.77 -815.87 -814.15
 -812.58 -808.24 -805.85 -803.92 -803.14 -802.15 -801.20
Pier Skew, UpSta & Num, DnSta & Num=  ,9985.00, 2 ,9997.10, 2 , 0 , 0 , 0 ,,
    2.00    2.00
 -818.51  181.49
    2.00    2.00
 -818.42  181.58
BR Coef=-1 , 0 , 0 ,, 0 ,,,0.8,0,1,0,
WSPro=,,,, 1 ,,,, 0 ,,,, 0 ,,,,-1 ,-1 ,-1 , 0 , 0 , 0 , 0 , 0
BC Design=,, 0 ,, 0 ,,,,,,

Type RM Length L Ch R = 1 ,6214.935,105.377400,105.377400,105.377400
XS GIS Cut Line= 6
790199.217663642824889.177751497790184.660585612824891.052526698
790018.086923629824853.471883431789801.744301558824745.808418959
789619.935243607824658.458815694789487.621641634824581.796428265
#Sta/Elev= 30
9496.536217.02729521.116214.79749531.368212.57289541.619211.64949603.127207.4274
9664.635204.46769685.421200.8015 9752.44200.7064 9808.29198.78099864.139198.1313
9908.818199.19539925.492197.85929931.107196.34239942.201187.57179975.484157.0894
9986.579154.30559997.673154.181210008.77156.194810019.86 162.95210030.96168.8782
10042.05173.584610053.14179.614110064.24183.465310075.33184.896610108.62186.0317
10119.71185.269510125.33185.391610200.38187.754110212.02187.284310278.25188.5946
#Mann= 3 , 0 , 0
9496.536    0.04       09496.536    0.04       010278.25    0.04       0
#XS Ineff= 2 , 0
       0                               0
Bank Sta=9496.536,10278.25
Exp/Cntr=0.3,0.1

Type RM Length L Ch R = 1 ,6109.557,228.569700,228.569700,228.569700
XS GIS Cut Line= 6
790209.766390414824794.239210565789971.562182152824707.842082913
789891.454192003824673.025789417789698.438288196824579.513709264
789622.466714323824547.612604032789524.615796397824516.083127063
#Sta/Elev= 30
9530.225218.73649567.101216.14919609.529215.62329641.349212.67069683.776211.9003
9715.745208.96869758.549203.61299779.951202.94719801.689199.51559812.592198.6206
  9834.4198.96839845.303198.27319856.207195.75159867.111190.0038 9878.16186.1393
 9900.42175.9237 9911.55173.60679956.069161.78819978.328159.15319989.458155.0923
10000.57154.712110022.74155.876510026.43157.625210033.83162.927110044.92172.4111
10056.01180.847210067.09185.228210110.87184.3145 10165.1185.319810270.68 189.017
#Mann= 3 , 0 , 0
9530.225    0.04       09530.225    0.04       010270.68    0.04       0
#XS Ineff= 2 , 0
       0                               0
Bank Sta=9530.225,10270.68
Exp/Cntr=0.3,0.1

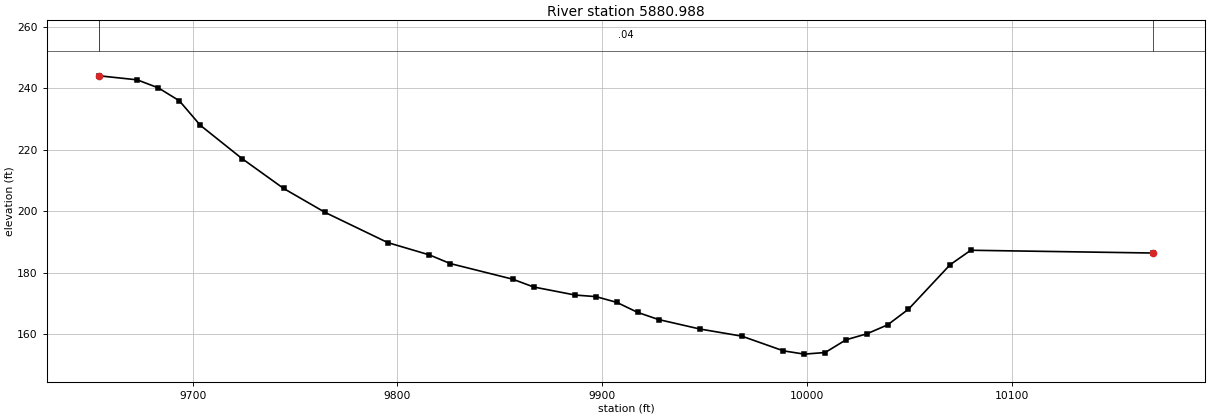
Type RM Length L Ch R = 1 ,5880.988,228.569700,228.569700,228.569700
XS GIS Cut Line= 6
790243.004010763824495.100627482 790198.72330986824484.551089663
  789904.7103086824429.811857738789832.199100734   824416.222287
789764.386055485824410.103348513789736.372162227824409.641994681
#Sta/Elev= 30
9654.415244.03449672.923242.72839683.202240.12199693.482235.92249703.722227.9541
9724.066 217.1369744.409207.40819764.753199.58669795.269189.79869815.612 185.794
9825.784182.9807  9856.3177.89529866.471175.36989886.815172.73799896.987172.2267
9907.159170.34649917.331167.09659927.502164.77739947.846161.6743 9968.19159.3741
9988.533154.59019998.705153.5252 10008.9154.048210019.07158.186510029.24160.1267
10039.41 163.04610049.58168.139110069.93182.6062   10080187.304810168.88186.4052
#Mann= 3 , 0 , 0
9654.415    0.04       09654.415    0.04       010168.88    0.04       0
#XS Ineff= 2 , 0
       0                               0
Bank Sta=9654.415,10168.88
Exp/Cntr=0.3,0.1