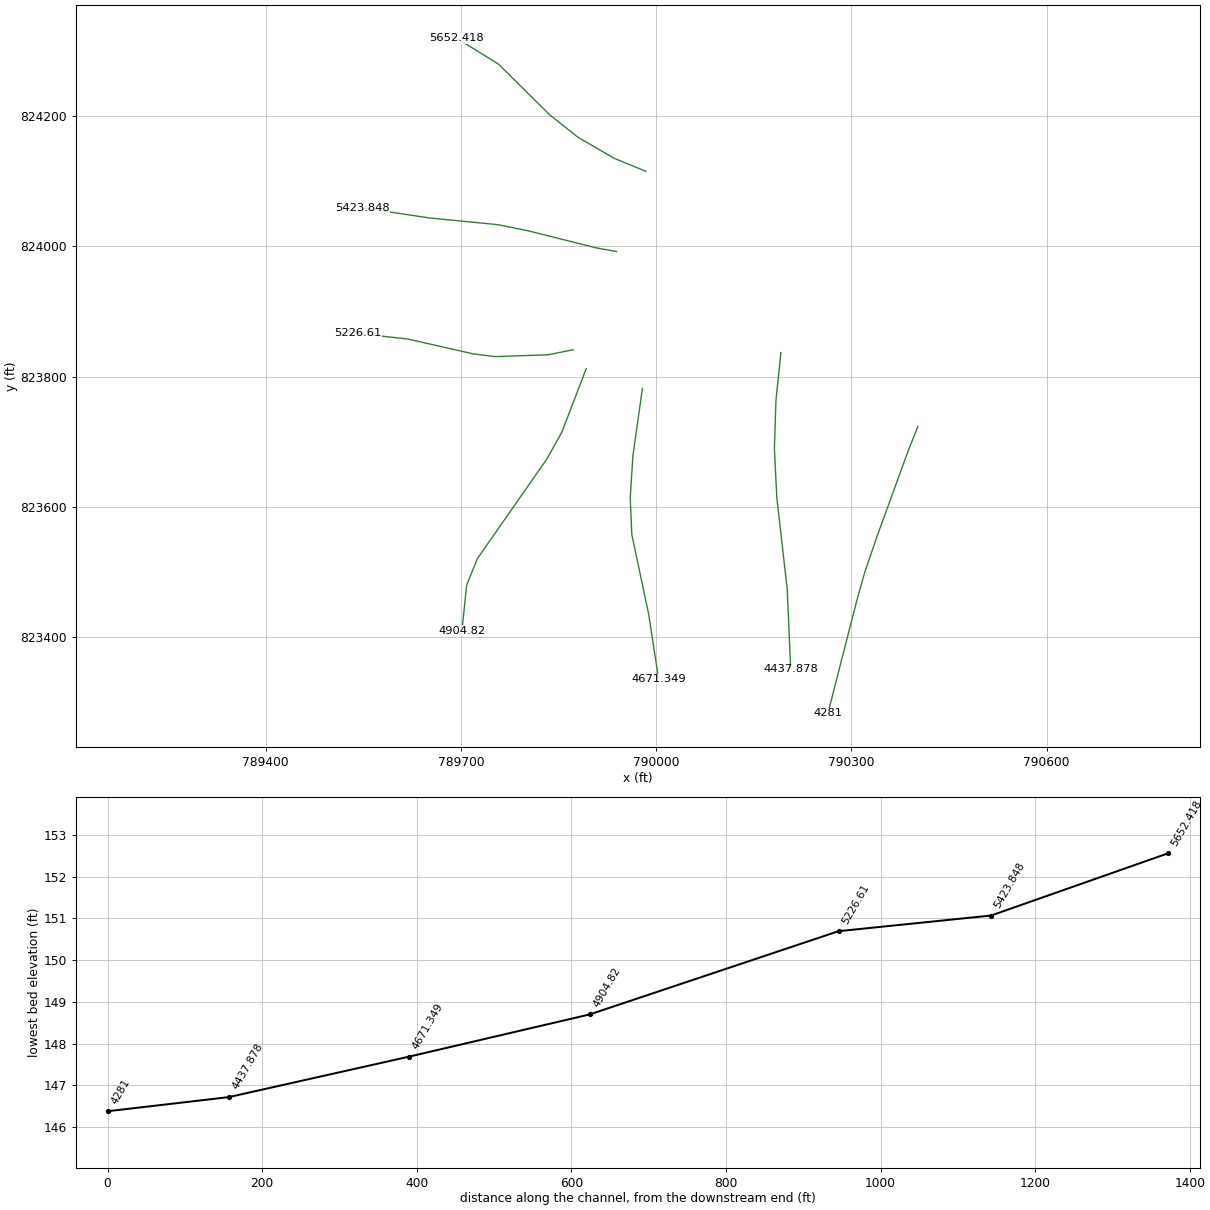
HEC-RAS study 18178_ras.prj: 18178

--- 18178_ras.g01 (geometry) --- (continued)

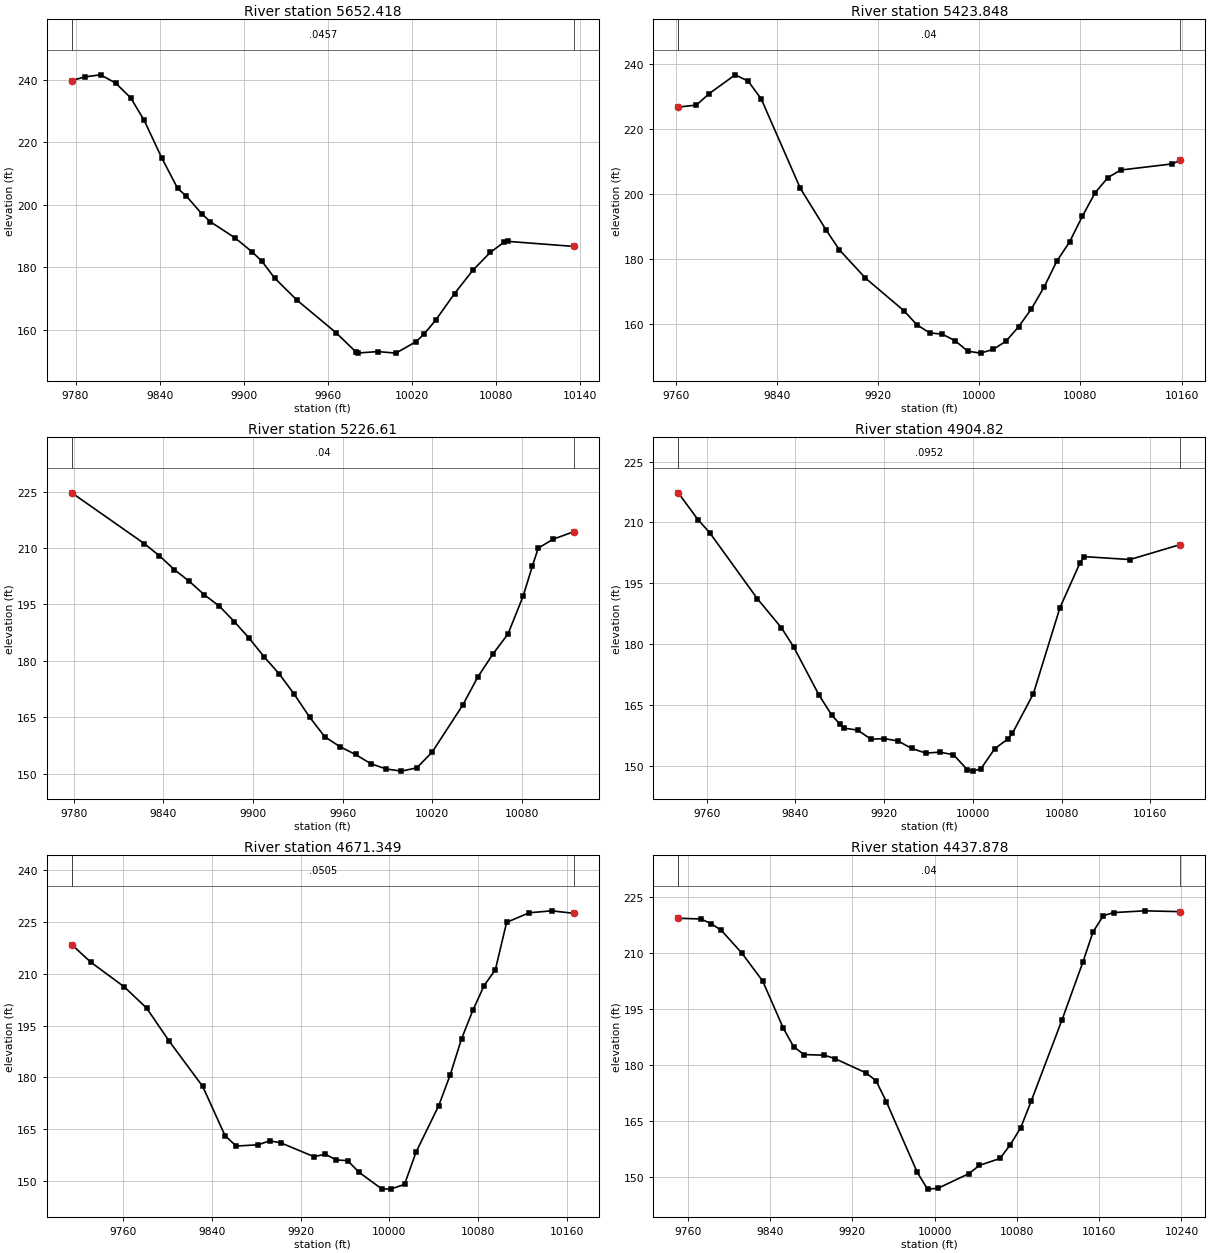
Type RM Length L Ch R = 1 ,5652.418,228.569700,228.569700,228.569700
XS GIS Cut Line= 6
789984.017970186824115.438198143789935.426214018824135.287587365
789879.986477974824167.494615575789836.131354664824202.373719984
 789757.78683959 824280.00028081789693.737236528824319.593415053
#Sta/Elev= 30
9777.297239.66739787.039240.87649797.841241.49749808.643238.86879819.445234.1018
9829.026226.91489841.576214.93239852.883205.20839859.164202.70869870.451196.9224
 9876.22194.55169893.948 189.3669906.005184.93849913.096181.91629922.071176.5998
9938.136169.47799965.832159.14959980.071152.99929981.766152.60249995.813153.0521
10008.77152.559610023.25156.264210028.68158.575710037.11163.064210050.59171.5775
10063.76179.076710076.12 184.73310085.86187.979210088.47188.282610135.81186.6573
#Mann= 3 , 0 , 0
9777.297  0.0457       09777.297  0.0457       010135.81  0.0457       0
#XS Ineff= 2 , 0
       0                               0
Bank Sta=9777.297,10135.81
Exp/Cntr=0.3,0.1

Type RM Length L Ch R = 1 ,5423.848,197.238700,197.238700,197.238700
XS GIS Cut Line= 6
789939.131740877823992.001067549789907.394605192823997.802535054
789801.401707046824024.379979384789755.781462383824033.435932536
  789651.6931264824043.620381219789548.367551557824059.189289639
#Sta/Elev= 30
9761.932  226.779776.298227.36399786.464230.91389806.974236.67949817.283234.7279
9827.593229.24689858.522201.75069879.141188.7941 9889.45182.82339909.996174.1563
9940.582164.06359950.766159.76489960.819157.30279970.872156.89529980.925154.8758
9990.979151.662510001.03151.069910011.07152.232310021.11154.719110031.16159.1766
 10041.2164.647410051.25171.336410061.34179.334610071.45 185.24710081.56193.1637
10091.67200.393110101.79205.0748 10111.9207.387610152.35209.265310159.06210.3378
#Mann= 3 , 0 , 0
9761.932    0.04       09761.932    0.04       010159.06    0.04       0
#XS Ineff= 2 , 0
       0                               0
Bank Sta=9761.932,10159.06
Exp/Cntr=0.3,0.1

Type RM Length L Ch R = 1 , 5226.61,321.790100,321.790100,321.790100
XS GIS Cut Line= 6
 789872.77643435823841.195924916789833.731324818823833.379206168
789752.833335555823830.621629846789719.766414003823834.639372222
789618.506234153823857.611652404789541.179330884823866.190775002
#Sta/Elev= 30
9778.711224.68419827.296211.16649837.329207.94899847.362204.26459857.395201.1438
9867.421197.56329877.425194.56829887.429 190.4689897.433186.02149907.492181.0484
9917.565176.51899927.639171.10379937.799165.08079948.054159.80539958.309157.1651
9968.565155.1215 9978.82152.66619989.075151.2651 9999.33150.695110009.59151.5716
10019.84155.747210040.29168.2372 10050.4  175.7210060.51181.830710070.62187.1835
10080.73 197.24210086.89205.1944 10090.8 209.97110100.81212.356610114.65214.3581
#Mann= 3 , 0 , 0
9778.711    0.04       09778.711    0.04       010114.65    0.04       0
#XS Ineff= 2 , 0
       0                               0
Bank Sta=9778.711,10114.65
Exp/Cntr=0.3,0.1

Type RM Length L Ch R = 1 , 4904.82,233.470800,233.470800,233.470800
XS GIS Cut Line= 6
789892.483252339823812.000639017789855.138117999823714.522303608
789832.090685248823673.328434558789725.357869482823520.248850312
789708.885818784823479.714661522789701.660851822823409.784374349
#Sta/Elev= 30
 9734.31 217.2979752.136210.68049762.622207.49739805.641191.20629827.418184.0132
9838.307179.35779861.197167.47889872.656162.54729880.071160.28529884.114 159.282
9896.074158.81949908.134156.56679920.194156.71169932.434156.13859944.948154.2851
9957.462153.14689969.975153.37079982.489152.75479995.003149.069910000.55148.6993
10007.42149.331710019.76154.236510031.83156.657310035.59157.979510054.52 167.731
10078.55188.983210096.52199.966610100.43201.571410141.68200.8523 10187.1204.5474
#Mann= 3 , 0 , 0
 9734.31  0.0952       0 9734.31  0.0952       0 10187.1  0.0952       0
#XS Ineff= 2 , 0
       0                               0
Bank Sta=9734.31,10187.1
Exp/Cntr=0.3,0.1

Type RM Length L Ch R = 1 ,4671.349,233.470900,233.470900,233.470900
XS GIS Cut Line= 6
789978.869645183823781.820533401789964.323954427823678.390824918
789960.180443344823613.646130243 789962.57577257823557.441661475
789988.520885605823434.829550347790003.742627974823335.127807405
#Sta/Elev= 30
9714.105218.40739731.091213.37639761.387206.18899781.583200.0187 9801.78190.4867
9831.971177.38469852.012 163.1849862.033160.14639882.073 160.5169892.084161.6638
9902.093161.0969 9932.12157.07369942.159157.79059952.291156.12769962.422155.9262
9972.554152.57599993.049147.7636   10001147.687710013.61149.063610023.87158.3513
10044.39171.856910054.65180.7023 10064.9191.186310075.04199.381910085.18 206.564
10095.32211.155410105.46224.859310125.74227.622310145.96228.191610165.96227.4722
#Mann= 3 , 0 , 0
9714.105  0.0505       09714.105  0.0505       010165.96  0.0505       0
#XS Ineff= 2 , 0
       0                               0
Bank Sta=9714.105,10165.96
Exp/Cntr=0.3,0.1

Type RM Length L Ch R = 1 ,4437.878,156.877900,156.877900,156.877900
XS GIS Cut Line= 6
790191.693482502823836.704070432790184.074433886823763.606830652
790181.664511303823689.140614361790185.367021506823614.075651931
790201.451135836823472.346471285790206.648796225823350.287463657
#Sta/Elev= 30
9750.828219.3596 9772.65219.16319782.704217.93559792.758216.11069812.866209.9425
9832.933202.51569852.943189.87819862.948184.94239872.954182.80159892.964182.6363
9902.972181.73449933.009 177.9379943.021175.82279953.033170.21239983.104151.2645
9993.155146.715810003.22146.937510033.42150.876110043.48 153.07310063.62154.9433
10073.69158.660410083.75163.202110093.82 170.24210123.99192.186610144.04207.4998
10154.07215.730310164.09 220.04510174.12220.882510204.15221.349910238.87221.1285
#Mann= 3 , 0 , 0
9750.828    0.04       09750.828    0.04       010238.87    0.04       0
#XS Ineff= 2 , 0
       0                               0
Bank Sta=9750.828,10238.87
Exp/Cntr=0.3,0.1

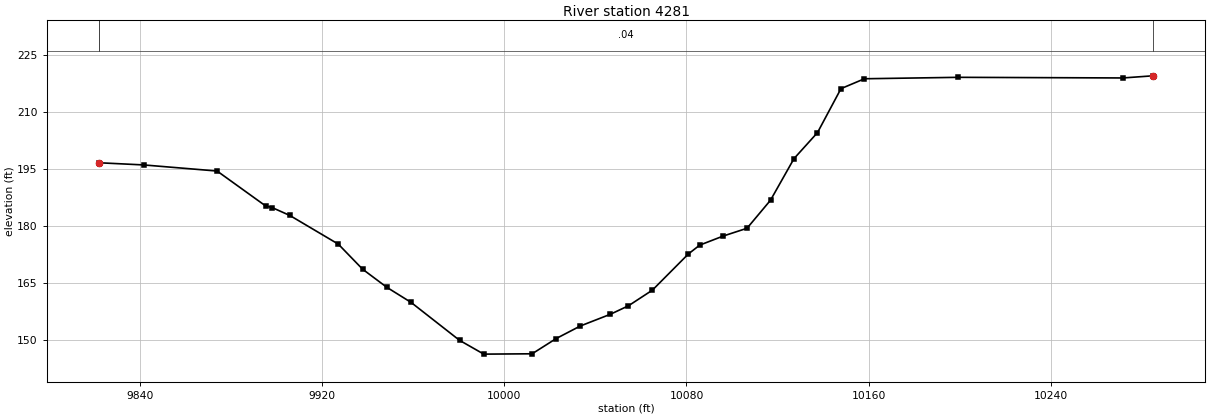
Type RM Length L Ch R = 1 ,    4281,0.000000,0.000000,0.000000
XS GIS Cut Line= 6
790402.097985164823723.138229079790387.749894705823687.326882049
790339.813557386 823555.62852003790320.554882176823499.516234481
790308.149110374823455.452391486790263.886821406823282.482621899
#Sta/Elev= 30
 9822.27196.7524 9841.81196.17979873.966 194.5769895.249 185.3969898.138184.9527
 9905.89182.88299927.173  175.339937.814168.74319948.456163.97039959.097159.9989
 9980.38150.01119991.021 146.37710012.24146.465710022.81150.482610033.38153.7789
10046.63156.879910054.53159.107410065.02163.216210080.82 172.74310085.79175.0686
10096.18177.477310106.57179.512510116.88186.899210127.19197.8478 10137.5204.6912
10147.81216.267610158.12  218.8710199.37 219.24710271.56 219.08110284.66219.6414
#Mann= 3 , 0 , 0
 9822.27    0.04       0 9822.27    0.04       010284.66    0.04       0
#XS Ineff= 2 , 0
       0                               0
Bank Sta=9822.27,10284.66
Exp/Cntr=0.3,0.1